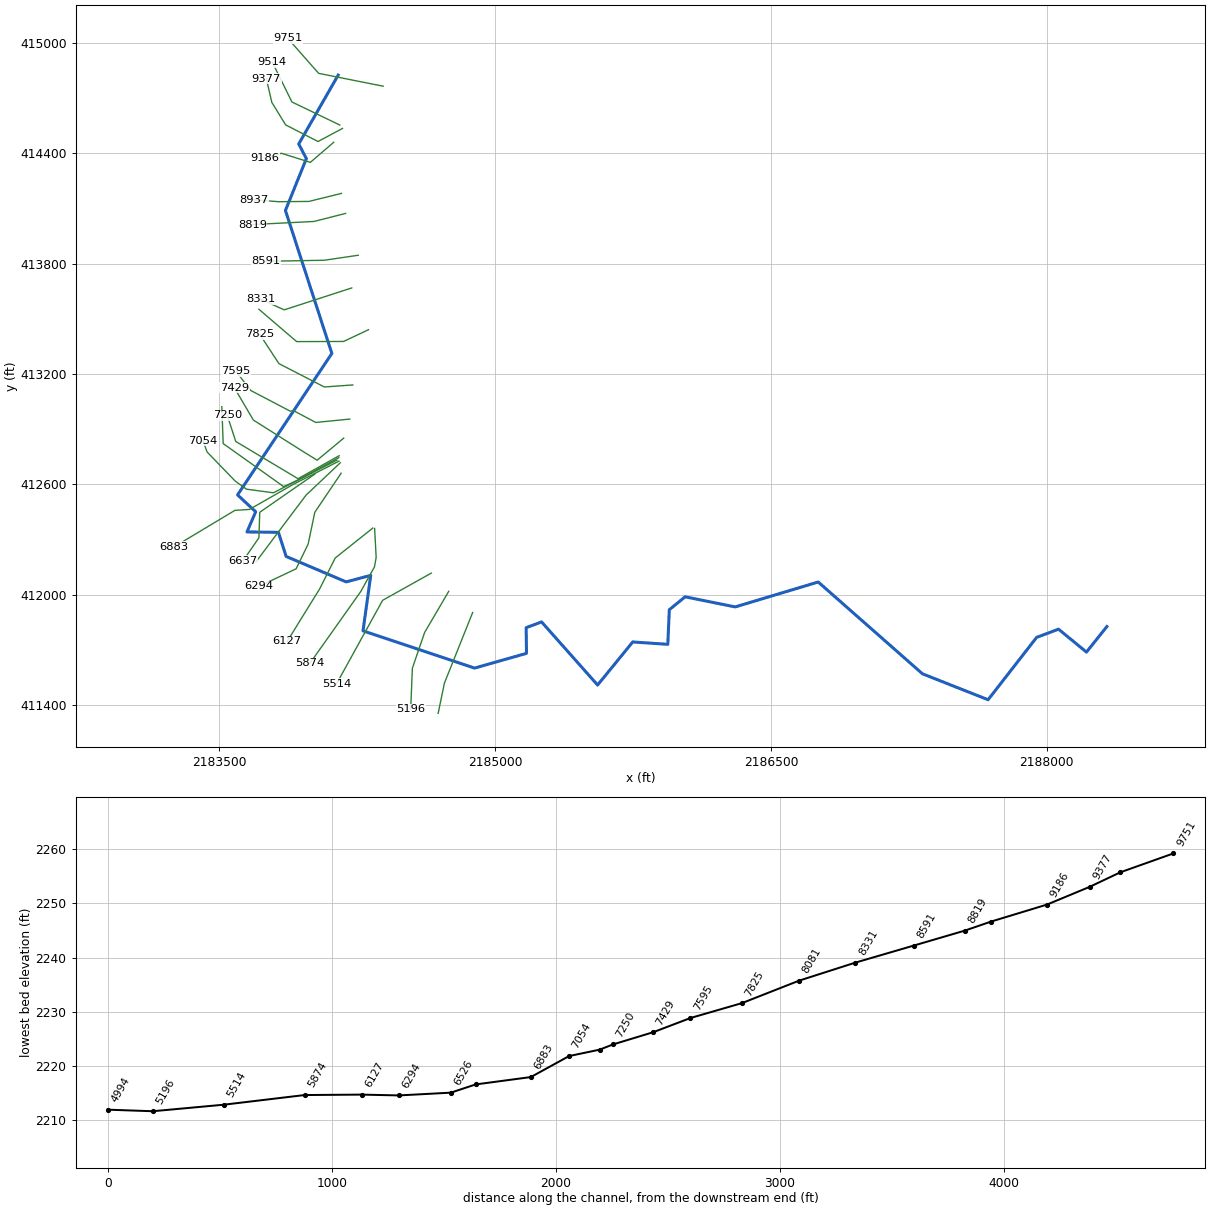
--- MLLSTNCK.prj (project) ---

Proj Title=MLLSTNCK
Current Plan=p01
Default Exp/Contr=0,0
English Units
Geom File=g01
Flow File=f01
Plan File=p01
Background Map Layer=Inundation Boundary (01pct Value_0)
BEGIN DESCRIPTION:
----------MODEL BY WOOD PLC 2021----------
Stream Name: Millstone Creek
Flood Zone: Enhanced Approximate
Pocahontas County, WV
HEC-RAS Version: RAS 6.1.0
Vertical Datum: NAVD88
Projection: NAD 1983 StatePlane West Virginia S FIPS 4702 (US Feet)
Terrain: 1-meter LIDAR (FEMA Region III 3DEP collected 2016-2018)
Land Use: 2019 NLCD
Hydrologic Method:
WV SIR2010-5033 regression equations
Model Notes:
Heavy Karst area, spotty floodplain and sinkholes throughout the reach
END DESCRIPTION:
DSS File=dss
DSS Export Rating Curves= 0
DSS Export Rating Curve Sorted= 0
DSS Export Volume Flow Curves= 0
DXF OffsetX= 0
DXF OffsetY= 0
DXF ScaleX= 0
DXF ScaleY= 0

--- MLLSTNCK.p01 (plan) ---

Plan Title=Floodplain
Program Version=6.10
Short Identifier=Floodplain
Geom File=g01
Flow File=f01
Subcritical Flow
K Sum by GR= 0
Std Step Tol= 0.01
Critical Tol= 0.01
Num of Std Step Trials= 20
Max Error Tol= 0.3
Flow Tol Ratio= 0.001
Split Flow NTrial= 30
Split Flow Tol= 0.02
Split Flow Ratio= 0.02
Log Output Level= 0
Friction Slope Method= 1
Unsteady Friction Slope Method= 2
Unsteady Bridges Friction Slope Method= 1
Parabolic Critical Depth
Global Vel Dist= 0 , 0 , 0
Global Log Level= 0
CheckData=True
Encroach Param=-1 ,0,0, 0
Computation Interval=0.1SEC
Output Interval=1SEC
Instantaneous Interval=Max Profile
Mapping Interval=1HOUR
Computation Time Step Use Courant=        0
Computation Time Step Use Time Series=    0
Computation Time Step Count To Double=0
Computation Time Step Max Doubling=0
Computation Time Step Max Halving=0
Computation Time Step Residence Courant=0
Run HTab= 0
Run UNet= 0
Run Sediment= 0
Run PostProcess= 0
Run WQNet= 0
Run RASMapper=-1
UNET Theta= 0
UNET Theta Warmup= 0
UNET ZTol= 0
UNET ZSATol= 0
UNET MxIter= 0
UNET Max Iter WO Improvement= 0
UNET MaxInSteps= 0
UNET DtIC= 0
UNET DtMin= 0
UNET MaxCRTS= 0
UNET WFStab= 0
UNET SFStab= 0
UNET WFX= 1
UNET SFX= 1
UNET Gravity=32.174
UNET 1D Methodology=Finite Difference
UNET DSS MLevel= 1
UNET Pardiso=0
UNET DZMax Abort= 0
UNET Use Existing IB Tables= 0
UNET Froude Reduction=False
UNET Froude Limit= 0
UNET Froude Power= 0
UNET D1 Cores= 0
UNET WindReference=Eulerian
UNET WindDragFormulation=Hsu (1988)
UNET D2 Coriolis=0
UNET D2 Cores= 0
UNET D2 Theta= 1
UNET D2 Theta Warmup= 1
UNET D2 Z Tol= 0.01
UNET D2 Volume Tol= 0.01
UNET D2 Max Iterations= 20
UNET D2 Equation= 0
UNET D2 RampUpFraction=0.1
UNET D2 TimeSlices= 1
UNET D2 Turbulence Formulation=Non-Conservative (original)
UNET D2 Eddy Viscosity=0.3
UNET D2 Transverse Eddy Viscosity=0.1
UNET D2 Smagorinsky Mixing=0
UNET D2 BCVolumeCheck=0
UNET D2 Cores=0
UNET D2 SolverType=PARDISO (Direct)
UNET D2 Minimum Iterations= 2147483647
UNET D2 Maximum Iterations= 2147483647
UNET D2 Restart Number= 10
UNET D2 Relaxation Coeff=1.3
UNET D2 SOR Precondition Iterations= 10
UNET D2 ILUT Maximum Fill= 8
UNET D2 ILUT Tolerance=1E-08
UNET D1D2 MaxIter= 0
UNET D1D2 ZTol=0.01
UNET D1D2 QTol=0.1
UNET D1D2 MinQTol=1
DSS File=dss
Write IC File= 0
Write IC File at Fixed DateTime=0
Write IC File at Sim End=0
Echo Input=False
Echo Parameters=False
Echo Output=False
Write Detailed= 0
HDF Write Warmup=0
HDF Write Time Slices=0
HDF Flush=0
HDF Compression= 1
HDF Chunk Size= 1
HDF Spatial Parts= 1
HDF Use Max Rows=0
HDF Fixed Rows= 1
Calibration Method= 0
Calibration Iterations= 20
Calibration Max Change=0.05
Calibration Tolerance=0.2
Calibration Maximum=1.5
Calibration Minimum=0.5
Calibration Optimization Method= 1
WQ AD Non Conservative
WQ ULTIMATE=-1
WQ Max Comp Step=1HOUR
WQ Output Interval=15MIN
WQ Output Selected Increments= 0
WQ Output face flow=0
WQ Output face velocity=0
WQ Output face area=0
WQ Output face dispersion=0
WQ Output cell volume=0
WQ Output cell surface area=0
WQ Output cell continuity=0
WQ Output cumulative cell continuity=0
WQ Output face conc=0
WQ Output face dconc_dx=0
WQ Output face courant=0
WQ Output face peclet=0
WQ Output face adv mass=0
WQ Output face disp mass=0
WQ Output cell mass=0
WQ Output cell source sink temp=0
WQ Output nsm pathways=0
WQ Output nsm derived pathways=0
WQ Create Restart=0
WQ Fixed Restart=0
WQ System Summary=0
WQ Write To DSS=0
Sorting and Armoring Iterations= 10
XS Update Threshold= 0.02
Bed Roughness Predictor= 0
Hydraulics Update Threshold= 0.02
Energy Slope Method= 1
Volume Change Method= 1
Sediment Retention Method= 0
Sediment TS Multiplier= 1
Warm Up Method= 0
XS Weighting Method= 0
Number of US Weighted Cross Sections= 1
Number of DS Weighted Cross Sections= 1
Upstream XS Weight=0
Main XS Weight=1
Downstream XS Weight=0
Number of DS XS's Weighted with US Boundary= 1
Upstream Boundary Weight= 1
Weight of XSs Associated with US Boundary= 0
Number of US XS's Weighted with DS Boundary= 1
Downstream Boundary Weight= 0.5
Weight of XSs Associated with DS Boundary= 0.5
Percentile Method= 0
Sediment Output Level= 3
Mass or Volume Output= 0
Output Increment Type= 1
Profile and TS Output Increment= 1
Transport Output Increment 1
XS Output Flag= 0
XS Output Increment= 10
Read HDF5 Sediment Hotstart= 0
Sediment Hotstart Type= 0
Write Gradation File= 0
Read Gradation Hotstart= 0
Write HDF5 File= 1
Write Binary Output= 1
Write DSS Sediment File= 0
DSS Sediment Output Type= 1
SV Curve= 0
Specific Gage Flag= 0
Subcell Erosion Methods= 0
Subcell Deposition Methods= 0
Advection Scheme= 1
Matrix Solver= 0
Implicit Weighting Factor= 1
Maximum Outer Loop Convergence Iterations= 5
Convergence Maximum Absolute= 0.001
Convergence RMSE= 0.0001
Grain Fractions Max Abs Error= 0.001
Max Subgrid Regions= 1
Max Subgrid Length Scale= 3.402823E+38
Initial Layer Thickness= 3.402823E+38
Min Layer Thickness= 3.402823E+38
Max Layer Thickness= 3.402823E+38
Number of Layers= 5

--- MLLSTNCK.f01 (steady flow) ---

Flow Title=Flow
Program Version=6.10
Number of Profiles= 6
Profile Names=01pct,10pct,04pct,02pct,0_2pct,01plus
River Rch & RM=MLLSTNCK,Main            ,9751
     526     277     369     445     735     777
River Rch & RM=MLLSTNCK,Main            ,9377
     574     303     403     486     801     848
River Rch & RM=MLLSTNCK,Main            ,6637
     636     337     448     539     886     940
River Rch & RM=MLLSTNCK,Main            ,5514
     803     430     568     681    1110    1190
River Rch & RM=MLLSTNCK,Main            ,4994
     893     490     633     759    1240    1320
Boundary for River Rch & Prof#=MLLSTNCK,Main            , 1
Up Type= 0
Dn Type= 3
Dn Slope=0.01397
Boundary for River Rch & Prof#=MLLSTNCK,Main            , 2
Up Type= 0
Dn Type= 3
Dn Slope=0.01397
Boundary for River Rch & Prof#=MLLSTNCK,Main            , 3
Up Type= 0
Dn Type= 3
Dn Slope=0.01397
Boundary for River Rch & Prof#=MLLSTNCK,Main            , 4
Up Type= 0
Dn Type= 3
Dn Slope=0.01397
Boundary for River Rch & Prof#=MLLSTNCK,Main            , 5
Up Type= 0
Dn Type= 3
Dn Slope=0.01397
Boundary for River Rch & Prof#=MLLSTNCK,Main            , 6
Up Type= 0
Dn Type= 3
Dn Slope=0.01397
DSS Import GetInterval= 0
DSS Import GetPeak= 0
DSS Import FillOption= 0

--- MLLSTNCK.g01 (geometry) ---

Geom Title=Geometry
Program Version=6.10

River Reach=MLLSTNCK        ,Main
Reach XY= 30
2184148.37913381414824.7523151212183933.89646034414450.381896516
2183975.39341866414370.6975532332183861.59501148414089.129234795
2184113.88633478413311.8886595772183601.38520287412543.089407105
2183699.93934458412451.5285350112183652.63901596412341.957030186
  2183823.738912412339.6569058082183865.24751784412208.832397108
 2184191.5723374412070.4289132982184325.24568616412105.865883031
     2184283.213      411804.3092184889.58419224411601.916711634
     2185171.798       411681.97     2185170.001      411821.493
     2185253.822      411852.789     2185558.223      411509.778
     2185749.196      411743.8672185939.85559069  411731.0945024
     2185947.989      411919.022 2186033.9131035411989.295670425
2186305.98905637411934.360825917      2186757.31      412069.778
 2187323.7879944411570.8501746092187680.56252765411429.845086041
2187944.45216331411768.8576855382188063.50058892  411813.3277392
2188215.12923395411688.767637634     2188326.223      411827.719

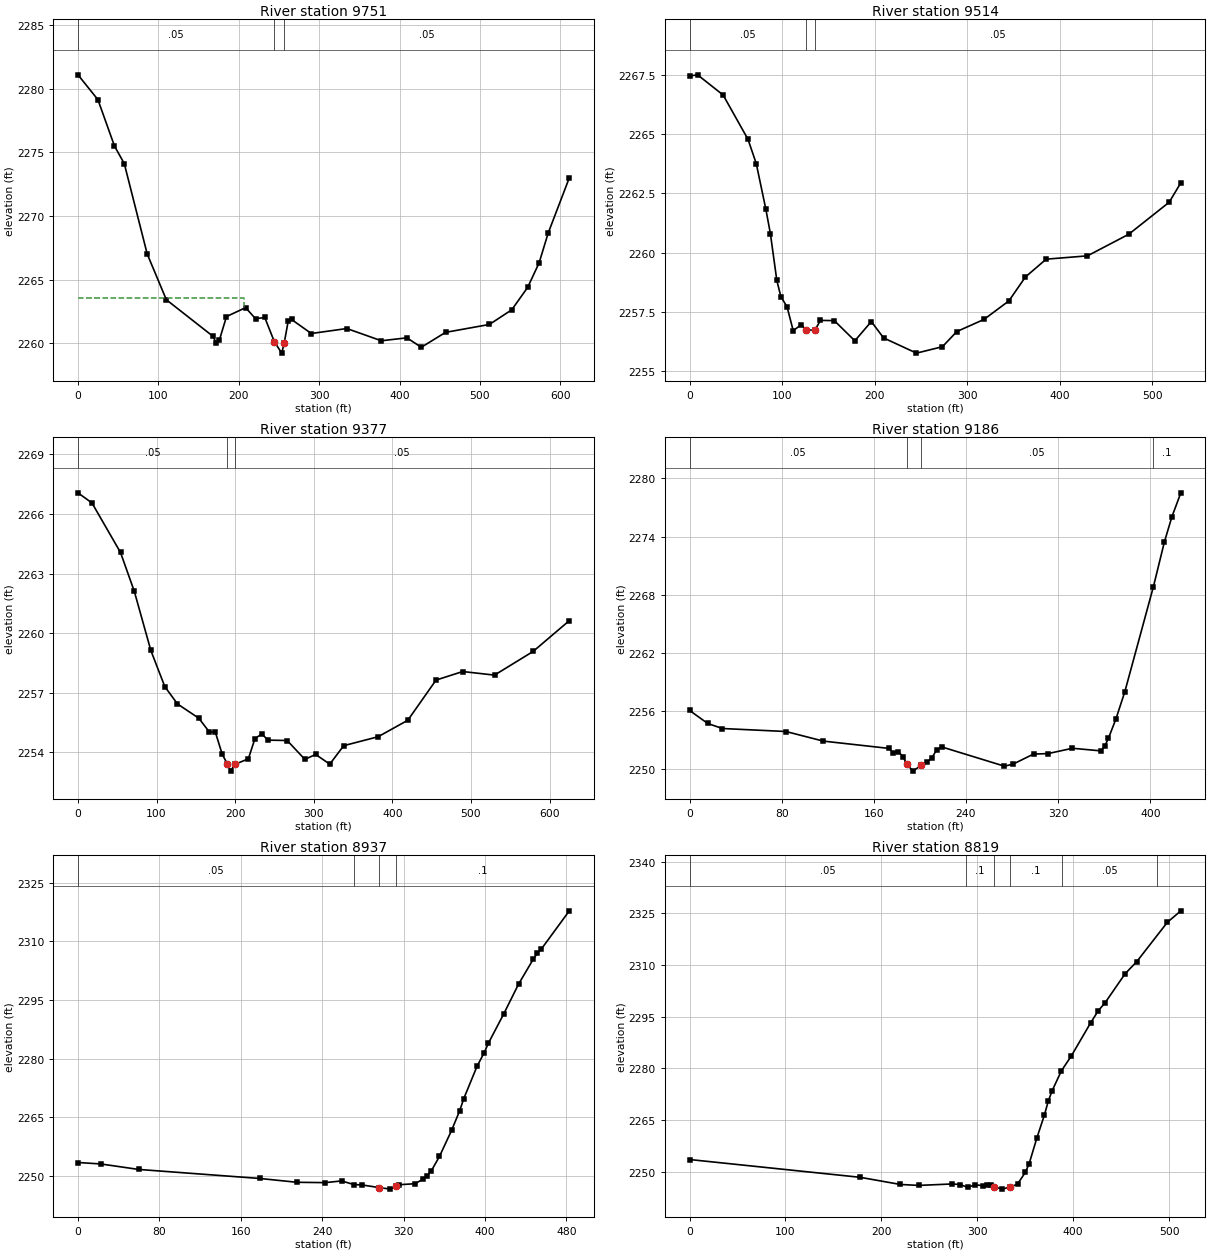
Type RM Length L Ch R = 1 ,9751    ,236.4,236.4,236.4
XS GIS Cut Line= 3
2184392.69753511414764.4952761642184042.16048703414834.225764223
2183874.43039413415024.571150548
#Sta/Elev= 30
       0 2281.08    24.8 2279.13    45.4 2275.49    57.6 2274.11    86.1 2267.02
   109.9 2263.43   167.7 2260.57   171.8 2260.06   175.9 2260.27   184.7 2262.11
   208.5 2262.81   220.8 2261.94   232.3 2262.04   244.2 2260.14   253.4 2259.24
   256.62260.072   261.5 2261.77   265.6 2261.88   290.2 2260.78   334.4 2261.17
   377.3 2260.21   409.1 2260.44     427  2259.7   457.2 2260.87   511.7 2261.49
   539.5 2262.64   559.3  2264.4   573.5 2266.32   584.8 2268.66   611.1    2273
#Mann= 3 ,-1,0
       0     .05       0   244.2    .045       0   256.6     .05       0
#XS Ineff= 2 , 0
          206.27 2263.56
Permanent Ineff=
       F       F
Bank Sta=244.2,256.6
XS Rating Curve= 0 ,0
Exp/Cntr(USF)=0,0
Exp/Cntr=0.3,0.1

Type RM Length L Ch R = 1 ,9514    ,137.3,137.8,136.7
XS GIS Cut Line= 3
2184157.12156194414553.4192041992183896.88398631414678.669402499
2183789.75830037414895.630379793
#Sta/Elev= 30
       0 2267.44     8.7 2267.49    36.3 2266.64    63.2 2264.77    72.1 2263.75
    82.5 2261.82    87.4 2260.79    94.3 2258.83    98.7 2258.14   105.4 2257.71
     112 2256.71   120.9 2256.96   125.42256.745   135.4 2256.72   141.4 2257.14
   156.4 2257.13   178.6 2256.28   196.4 2257.09   209.7  2256.4   245.2 2255.76
   273.2 2256.03   288.8 2256.67   318.1 2257.18     345 2257.96   362.9 2258.97
   385.3 2259.72   429.9 2259.86   474.5 2260.77   518.2 2262.12   530.8 2262.94
#Mann= 3 ,0,0
       0     .05       0   125.4    .045       0   135.4     .05       0
Bank Sta=125.4,135.4
XS Rating Curve= 0 ,0
Exp/Cntr(USF)=0,0
Exp/Cntr=0.3,0.1

Type RM Length L Ch R = 1 ,9377    ,187.3,190.2,189.5
XS GIS Cut Line= 5
2184171.88891369 414534.927697722184038.66454407414463.810615081
2183862.72491763414554.1752102342183787.71481513414676.326601751
2183757.58471143414805.956647442
#Sta/Elev= 30
       0 2267.06    17.8 2266.55    54.1 2264.06    71.7  2262.1    92.7 2259.13
   110.5 2257.31   126.6 2256.44   153.8 2255.72   167.3 2255.02   174.7 2255.03
   183.6  2253.9   190.12253.424   194.3 2253.06   199.32253.395   216.8 2253.68
   225.2  2254.7   234.1 2254.93   241.6 2254.62   266.2  2254.6   288.7 2253.65
   302.4  2253.9   320.4 2253.41   338.1 2254.34   381.9 2254.79   419.7 2255.62
   455.6 2257.64   489.5 2258.07     530 2257.89   579.1 2259.08   625.2 2260.63
#Mann= 3 ,-1,0
       0     .05       0   190.1    .045       0   199.3     .05       0
Bank Sta=190.1,199.3
XS Rating Curve= 0 ,0
Exp/Cntr(USF)=0,0
Exp/Cntr=0.3,0.1

Type RM Length L Ch R = 1 ,9186    ,245.1,249.7,253.8
XS GIS Cut Line= 4
2184124.18558795414459.7480367052183997.02665395414350.407552062
2183839.90032787 414399.81325253 2183749.1882221414374.705437538
#Sta/Elev= 30
       0 2256.06    15.8 2254.71    28.5 2254.19    83.7 2253.88   116.1 2252.89
   172.8 2252.14   176.9 2251.69   181.2 2251.81   185.4 2251.27   188.42250.566
   193.8 2249.79   201.22250.384   206.3 2250.71   210.5 2251.19   214.7 2252.02
   218.9 2252.29   273.4  2250.3     281 2250.52   298.6 2251.55   311.2  2251.6
   332.4 2252.15   357.1 2251.88   360.3 2252.35   363.6 2253.17   370.1 2255.16
   377.8 2257.96   402.7 2268.84   412.3 2273.49   418.8 2276.07   426.5 2278.52
#Mann= 4 ,-1,0
       0     .05       0   188.4    .045       0   201.2     .05       0
  402.41      .1       0
Bank Sta=188.4,201.2
XS Rating Curve= 0 ,0
Exp/Cntr(USF)=0,0
Exp/Cntr=0.3,0.1

Type RM Length L Ch R = 1 ,8937    ,116.2,117.2,117.2
XS GIS Cut Line= 4
2184165.95730307414181.8521579072183989.73728831414138.206018902
2183824.49405798414136.6409965372183688.86057387414147.348903177
#Sta/Elev= 30
       0 2253.46    22.4 2253.09    59.5 2251.69     179 2249.37   215.1  2248.4
   243.1 2248.31   259.1 2248.75   271.1 2247.82   279.2 2247.72   296.32247.034
   307.1 2246.65   312.52247.407   315.1 2247.77   331.1 2248.03   338.7 2249.12
   343.1 2250.07   347.1 2251.25   355.3 2255.03   367.2 2261.68   375.2 2266.74
   379.2 2269.83   392.2 2278.07   399.3 2281.59   403.3 2283.95   418.3  2291.4
   433.1 2299.13   447.4 2305.44   451.4 2306.98   455.5  2308.1   482.9 2317.84
#Mann= 4 ,-1,0
       0     .05       0  271.54      .1       0   296.3    .045       0
   312.5      .1       0
Bank Sta=296.3,312.5
XS Rating Curve= 0 ,0
Exp/Cntr(USF)=0,0
Exp/Cntr=0.3,0.1

Type RM Length L Ch R = 1 ,8819    ,227.4,228.5,228.6
XS GIS Cut Line= 3
2184188.62374101 414072.901979652184016.21609446414029.218881745
2183682.20040002414012.536769791
#Sta/Elev= 30
       0 2253.57   177.9 2248.41   219.9 2246.33     239 2246.06     274 2246.48
     282 2246.32     290 2245.51     298 2246.23   306.1 2245.98   310.1 2246.32
   314.1 2246.27     317 2245.67   326.1 2244.98   334.3 2245.62     342 2246.42
   350.1 2249.83   354.1 2252.34   362.1 2259.76   370.1 2266.54   374.1 2270.54
   378.1 2273.53   387.7 2279.28   398.2 2283.67   418.2 2293.21   426.2 2296.74
   433.5 2299.13   454.2 2307.48   466.3 2310.98   498.3 2322.42   512.3 2325.73
#Mann= 6 ,-1,0
       0     .05       0  287.86      .1       0     317    .045       0
   334.3      .1       0  387.86     .05       0  487.86      .1       0
Bank Sta=317,334.3
XS Rating Curve= 0 ,0
Exp/Cntr(USF)=0,0
Exp/Cntr=0.3,0.1

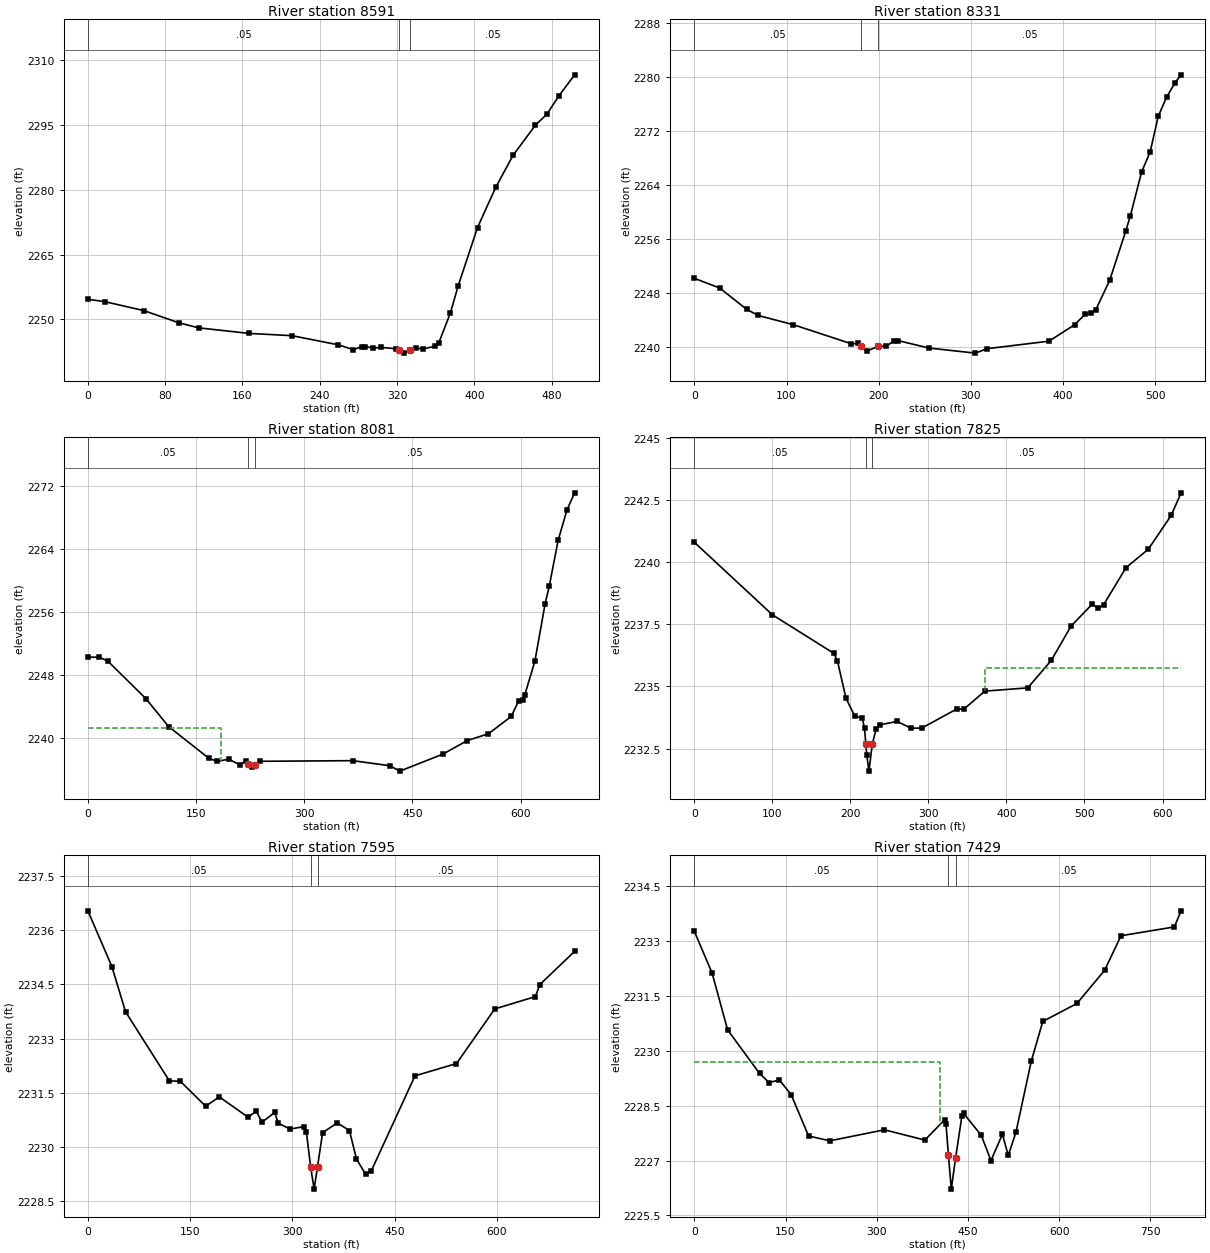
Type RM Length L Ch R = 1 ,8591    ,255.4,260,259.9
XS GIS Cut Line= 3
2184257.42908315413845.6524018132184072.31421159413818.422167895
2183755.70010365413812.768344539
#Sta/Elev= 30
       0 2254.68    17.4 2254.14    57.9 2252.06    94.3 2249.23   114.5 2248.07
   166.8 2246.78   211.3 2246.25   259.2 2244.13   274.9 2243.01   283.3 2243.72
   287.3 2243.71   295.3 2243.38   303.3 2243.54   319.3 2243.22   322.1 2242.84
   327.3 2242.21   333.9 2242.92   339.3 2243.36   347.3 2243.21   359.3  2243.8
   363.3 2244.63   375.3 2251.57   383.3 2257.81   403.3  2271.3   422.2 2280.63
     440 2287.99   463.3 2295.03   475.3  2297.6   487.4 2301.75   503.8 2306.67
#Mann= 3 ,-1,0
       0     .05       0   322.1    .045       0   333.9     .05       0
Bank Sta=322.1,333.9
XS Rating Curve= 0 ,0
Exp/Cntr(USF)=0,0
Exp/Cntr=0.3,0.1

Type RM Length L Ch R = 1 ,8331    ,252.3,250.4,244.6
XS GIS Cut Line= 3
2184222.19529648413668.0311416882183855.13301958413548.930474674
2183725.54637908413607.346095931
#Sta/Elev= 30
       0 2250.16    27.4 2248.73    56.8 2245.56    69.4 2244.65   107.3 2243.29
   170.3 2240.46   177.7 2240.51   180.72240.141   187.2 2239.38   199.62240.089
   208.2 2240.08   216.6 2240.91   220.8 2240.93   254.7 2239.82   304.9 2239.07
   317.5 2239.73   384.7 2240.84   412.5 2243.28   424.2 2244.87   430.7 2244.98
   435.2 2245.42   450.6 2249.88   468.1 2257.22     473 2259.43   485.1  2265.9
   494.4 2268.88   503.2 2274.16   512.3 2277.02   521.4 2279.16     528 2280.33
#Mann= 3 ,-1,0
       0     .05       0   180.7    .045       0   199.6     .05       0
Bank Sta=180.7,199.6
XS Rating Curve= 0 ,0
Exp/Cntr(USF)=0,0
Exp/Cntr=0.3,0.1

Type RM Length L Ch R = 1 ,8081    ,258.8,255.9,249
XS GIS Cut Line= 4
2184313.02937974413440.9302790262184177.79079886413377.100205037
2183922.64298923413376.3032546992183717.38602737413552.070549585
#Sta/Elev= 30
       0 2250.23    15.5 2250.24    27.5 2249.75    80.6 2244.95   111.9 2241.42
   167.3 2237.41   179.2 2236.98   195.2 2237.27   211.2 2236.53   219.2 2237.07
   222.52236.615   227.2 2236.28   231.92236.579   239.2    2237   367.2 2237.08
   418.5 2236.44   432.6 2235.75   492.2 2237.91   526.2 2239.64   555.4  2240.5
     587  2242.7   597.1 2244.63   602.8 2244.84   605.6 2245.38   619.8 2249.72
     634 2257.03   639.7 2259.24     652 2265.07   664.3 2268.96   674.9 2271.13
#Mann= 3 ,-1,0
       0     .05       0   222.5    .045       0   231.9     .05       0
#XS Ineff= 2 , 0
          184.21 2241.25
Permanent Ineff=
       F       F
Bank Sta=222.5,231.9
XS Rating Curve= 0 ,0
Exp/Cntr(USF)=0,0
Exp/Cntr=0.3,0.1

Type RM Length L Ch R = 1 ,7825    ,221.6,229.7,233.6
XS GIS Cut Line= 4
2184228.03398398 413140.828336132184072.83800047413129.703463349
2183826.25218368 413256.657953092183721.71331596413416.361076225
#Sta/Elev= 30
       0  2240.8   100.1 2237.88   178.8 2236.33   183.3 2236.04   194.3 2234.53
   205.8 2233.79   215.1 2233.74   218.1 2233.31  219.832232.664     221 2232.23
   223.8 2231.59     2282232.665   232.9 2233.28   237.3 2233.45   259.8 2233.59
   277.5 2233.32   291.3 2233.32   336.3 2234.09   345.3 2234.08   372.3 2234.81
   427.3 2234.94   457.5 2236.05   482.9 2237.43   509.9 2238.31   517.1 2238.15
   524.4 2238.28   553.3 2239.78   581.8 2240.52   611.1 2241.88   623.8 2242.79
#Mann= 3 ,0,0
       0     .05       0  219.83    .045       0     228     .05       0
#XS Ineff= 2 , 0
                          371.89         2235.75
Permanent Ineff=
       F       F
Bank Sta=219.83,228
XS Rating Curve= 0 ,0
Exp/Cntr(USF)=0,0
Exp/Cntr=0.3,0.1

Type RM Length L Ch R = 1 ,7595    ,172.6,166.2,159.7
XS GIS Cut Line= 6
 2184211.1766586412955.2968243112184026.68931651412936.881196959
2183905.96184091413000.8159864522183887.55445063 412998.33806853
2183672.29232096413111.0253701912183593.23229392413214.938256398
#Sta/Elev= 30
       0 2236.53    35.2 2234.99    55.3 2233.74   119.6 2231.83   135.7 2231.82
   172.8 2231.13   192.8 2231.39   234.8 2230.83   247.1 2230.99   255.5 2230.69
   274.2 2230.96   279.2 2230.66   296.9  2230.5   317.7 2230.57   320.6 2230.41
   326.8 2229.46   331.9 2228.84   336.92229.459   344.4  2230.4   365.9 2230.67
   383.7 2230.46   394.1 2229.67   407.6 2229.25   415.7 2229.34   479.9 2231.97
   540.8 2232.31     597 2233.82   656.6 2234.16     663 2234.49   714.1 2235.41
#Mann= 3 ,0,0
       0     .05       0   326.8    .045       0   336.9     .05       0
Bank Sta=326.8,336.9
XS Rating Curve= 0 ,0
Exp/Cntr(USF)=0,0
Exp/Cntr=0.3,0.1

Type RM Length L Ch R = 1 ,7429    ,176.1,178.8,177.1
XS GIS Cut Line= 5
2184178.62210411412851.8042161662184034.04172215412731.723177346
2183956.76632783412779.3959360672183687.18980428412950.072445221
2183584.50866068413124.744898634
#Sta/Elev= 30
       0 2233.26    29.2 2232.12    54.7 2230.57   107.2 2229.38   122.8 2229.13
   139.9  2229.2   159.2  2228.8   187.9 2227.67     223 2227.54   312.6 2227.84
     379 2227.56     412 2228.12   413.8    2228   417.82227.161   422.5 2226.22
   429.7 2227.08   439.9 2228.21   442.7 2228.29   471.8 2227.69   487.8    2227
   506.6 2227.72   516.2 2227.14   528.8 2227.77     554 2229.71     573  2230.8
   629.2 2231.29   674.8  2232.2   701.6 2233.14   789.3 2233.38   800.4 2233.82
#Mann= 3 ,0,0
       0     .05       0   417.8    .045       0   429.7     .05       0
#XS Ineff= 2 , 0
          403.94 2229.69
Permanent Ineff=
       F       F
Bank Sta=417.8,429.7
XS Rating Curve= 0 ,0
Exp/Cntr(USF)=0,0
Exp/Cntr=0.3,0.1

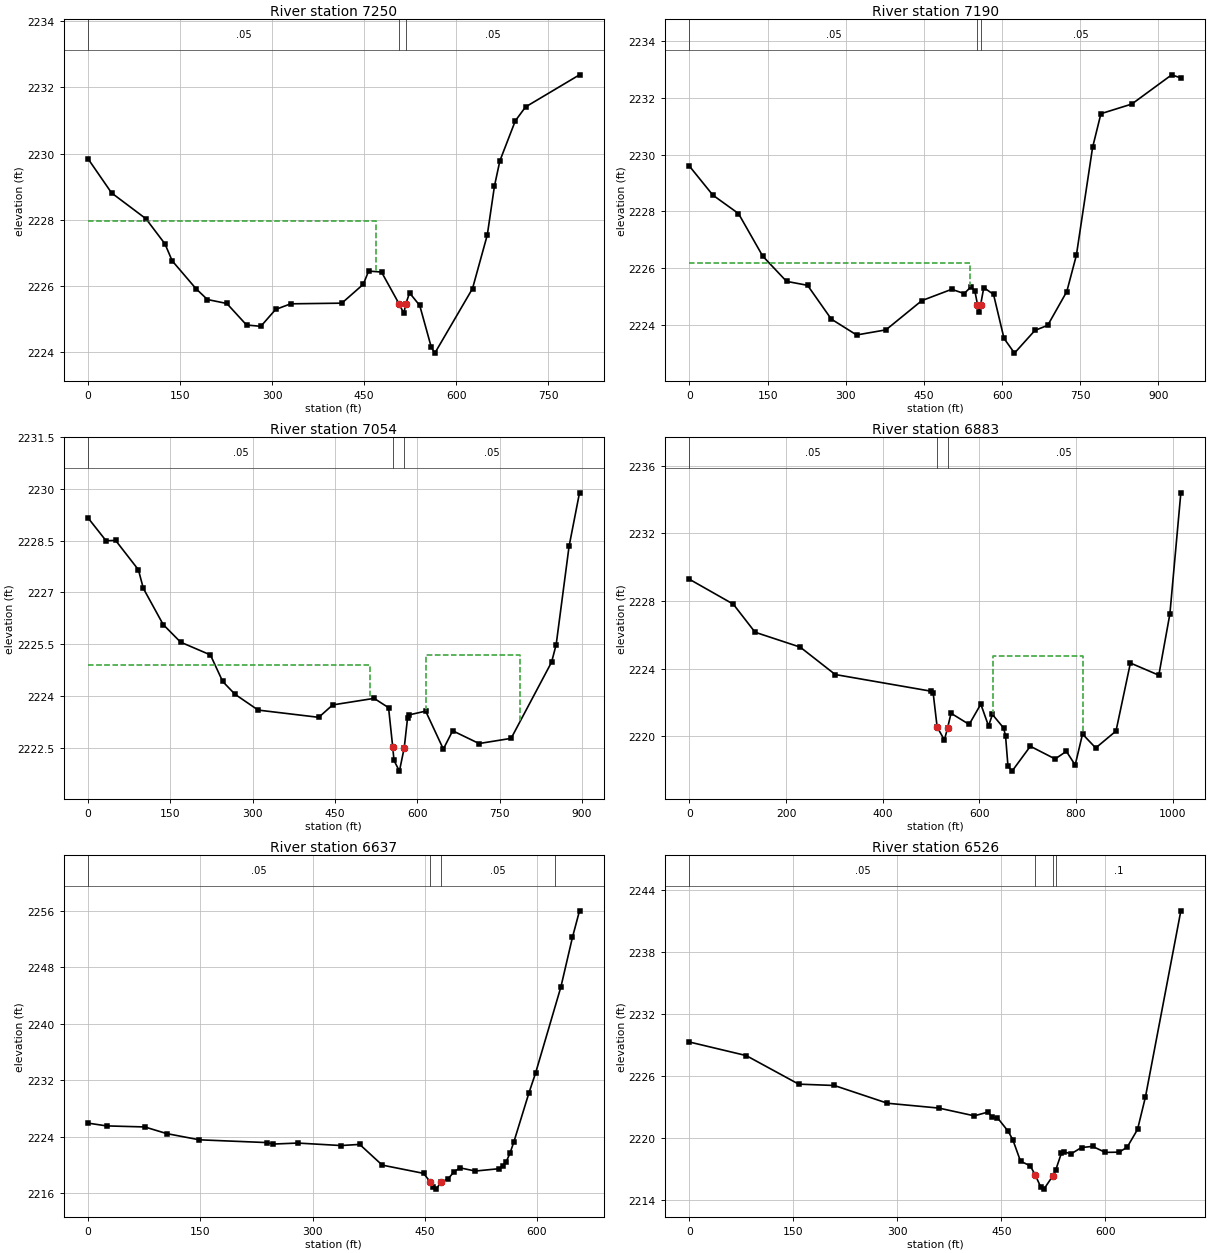
Type RM Length L Ch R = 1 ,7250    ,61,60.2,59.5
XS GIS Cut Line= 4
2184153.60512692412755.993070889 2183930.0443282412631.135319912
2183591.52509846412833.6796790862183545.12517221412976.656196013
#Sta/Elev= 30
       0 2229.84    38.3 2228.81    94.3 2228.03   125.3 2227.27     137 2226.76
   175.7 2225.92   194.4 2225.59   226.1 2225.47   258.2 2224.82   281.5 2224.78
   305.6 2225.29   330.2 2225.46   413.5 2225.48   448.5 2226.05   457.2 2226.45
   478.2 2226.42   506.8 2225.46   514.6 2225.17  517.682225.454   523.9 2225.79
   540.5 2225.41   559.3 2224.15   565.1 2223.97   626.5 2225.92   650.6 2227.54
   662.3 2229.02   671.1 2229.78   696.3 2230.99     713 2231.41   800.9 2232.38
#Mann= 3 ,0,0
       0     .05       0   506.8    .045       0  517.68     .05       0
#XS Ineff= 2 , 0
           469.3 2227.95
Permanent Ineff=
       F       F
Bank Sta=506.8,517.68
XS Rating Curve= 0 ,0
Exp/Cntr(USF)=0,0
Exp/Cntr=0.3,0.1

Type RM Length L Ch R = 1 ,7190    ,136.5,136,133.6
XS GIS Cut Line= 6
2184151.52813507412745.5285691462183932.85221257412625.753356419
2183851.67132421 412587.488565662183829.76535965412604.065599322
2183523.35302094412822.0680262622183515.82473025413022.425366525
#Sta/Elev= 30
       0 2229.59    44.9 2228.57    94.1 2227.92   140.6 2226.42   186.3 2225.53
   226.7 2225.39   272.2  2224.2   320.8 2223.64   377.1 2223.82   445.9 2224.85
   503.3 2225.25   527.2  2225.1   540.6 2225.34   547.9 2225.18   552.82224.711
     555 2224.44  558.772224.698   564.9 2225.31   583.6 2225.07   603.7 2223.52
   623.8    2223     663  2223.8   687.6 2223.98   724.2 2225.17   742.6 2226.45
   773.7 2230.25   789.7 2231.44     849 2231.78   925.5 2232.81   943.1  2232.7
#Mann= 3 ,0,0
       0     .05       0   552.8    .045       0  558.77     .05       0
#XS Ineff= 2 , 0
          539.18 2226.16
Permanent Ineff=
       F       F
Bank Sta=552.8,558.77
XS Rating Curve= 0 ,0
Exp/Cntr(USF)=0,0
Exp/Cntr=0.3,0.1

Type RM Length L Ch R = 1 ,7054    ,151.9,170.9,188.2
XS GIS Cut Line= 6
 2184141.1158057412731.9828251522183796.13262639412554.596331113
2183649.85895709412574.3792454042183588.11228521412618.740931998
2183435.84379339 412776.404764082183413.66295009412836.952471457
#Sta/Elev= 30
       0 2229.16    32.7  2228.5    50.1 2228.51    91.6 2227.66   100.6 2227.12
   136.8 2226.07   168.5 2225.56   222.8 2225.19   245.2 2224.42   267.5 2224.05
   309.8 2223.59   420.2 2223.38   445.6 2223.74   521.1 2223.93   547.4 2223.66
  555.012222.518   557.3 2222.13   567.2 2221.82     576  2222.5     582 2223.36
   584.6 2223.45     615 2223.56   647.2 2222.46   664.2 2222.99   712.3 2222.62
   770.7 2222.77   844.4 2224.98   852.8 2225.49   876.3 2228.34   895.3 2229.89
#Mann= 3 ,0,0
       0     .05       0  555.01    .045       0     576     .05       0
#XS Ineff= 2 ,-1
       0  514.37  2224.9  615.21  786.562225.196
Permanent Ineff=
       F       F
Bank Sta=555.01,576
XS Rating Curve= 0 ,0
Exp/Cntr(USF)=0,0
Exp/Cntr=0.3,0.1

Type RM Length L Ch R = 1 ,6883    ,228.9,246.2,254.6
XS GIS Cut Line= 5
2184152.63006667412726.5958461062183906.47499352412601.774066368
2183666.42337509412464.2863337862183587.06594926412459.094726488
2183257.02805676412261.071990988
#Sta/Elev= 30
       0 2229.28    90.7 2227.81   135.8 2226.15   229.2 2225.27   301.7 2223.65
   500.9 2222.66   504.5 2222.53   512.6 2220.55   527.6 2219.78  534.122220.483
   541.4 2221.36   578.9  2220.7     603  2221.9     619 2220.61     627 2221.29
   650.2 2220.49   654.2 2220.02   659.2 2218.24   667.7 2217.94   705.5 2219.41
   756.8 2218.66   780.1 2219.11   798.3  2218.3   813.5 2220.13   840.8 2219.31
   882.8 2220.31   912.6 2224.33   971.4 2223.61   994.3 2227.23    1017 2234.39
#Mann= 3 ,0,0
       0     .05       0   512.6    .045       0  534.12     .05       0
#XS Ineff= 1 ,-1
  627.56  814.132224.726
Permanent Ineff=
       F
Bank Sta=512.6,534.12
XS Rating Curve= 0 ,0
Exp/Cntr(USF)=0,0
Exp/Cntr=0.3,0.1

Type RM Length L Ch R = 1 ,6637    ,117.4,110.8,92.3
XS GIS Cut Line= 4
2184022.41930408412657.117461989  2183722.047739412448.711511893
2183717.59778989412310.0214312242183630.82378219412184.681197892
#Sta/Elev= 30
       0 2225.92    24.6 2225.53    75.8 2225.38     105 2224.44   148.8 2223.56
   238.5 2223.17   247.7 2222.96   280.2  2223.1   337.9 2222.75     363 2222.91
   393.1 2219.98   448.4 2218.81   457.2 2217.61   461.2 2216.85   465.2 2216.58
   471.6 2217.56   481.2 2218.04   489.2 2219.05   497.2 2219.59   517.5 2219.14
   549.2 2219.47   554.9 2219.86   558.9 2220.48   563.8 2221.64   569.2 2223.31
   589.3 2230.23     598 2232.98   631.9 2245.19   647.4 2252.23   656.8 2255.97
#Mann= 4 ,-1,0
       0     .05       0   457.2    .045       0   471.6     .05       0
  624.35      .1       0
Bank Sta=457.2,471.6
XS Rating Curve= 0 ,0
Exp/Cntr(USF)=0,0
Exp/Cntr=0.3,0.1

Type RM Length L Ch R = 1 ,6526    ,225.1,232.1,232.7
XS GIS Cut Line= 4
2184159.48847474412717.3470064552183974.21648791412542.425323493
2183861.92476886412393.4576064392183701.57026592412179.191188893
#Sta/Elev= 30
       0 2229.31    81.8    2228   157.6 2225.23     209  2225.1   285.7 2223.38
     360 2222.91     411 2222.16     431 2222.53   436.7    2222   444.3 2221.98
   459.9 2220.66   466.7 2219.82   477.7 2217.76   491.7 2217.32   499.12216.404
   506.6  2215.3   511.4 2215.06   524.4 2216.35   528.5 2216.92   536.6 2218.53
     540 2218.65   551.1  2218.5   565.7 2219.09   581.6  2219.2     600 2218.62
     620 2218.64   631.6 2219.13   646.5 2220.84   657.9 2223.98     709 2242.02
#Mann= 4 ,-1,0
       0     .05       0   499.1    .045       0   524.4     .05       0
   528.5      .1       0
Bank Sta=499.1,524.4
XS Rating Curve= 0 ,0
Exp/Cntr(USF)=0,0
Exp/Cntr=0.3,0.1

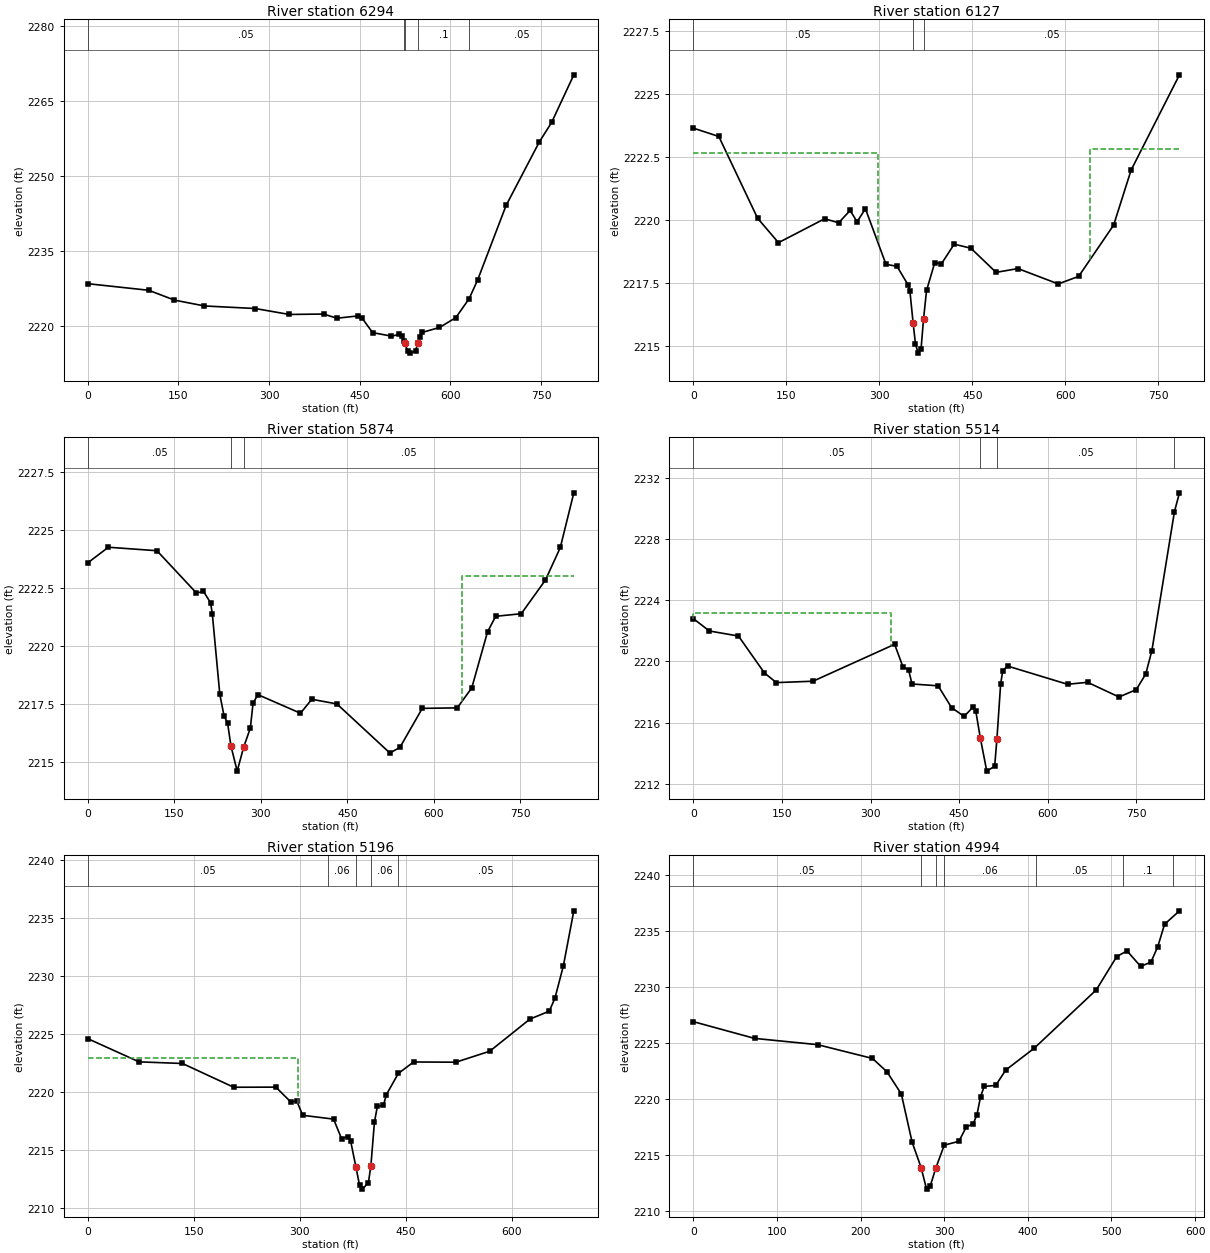
Type RM Length L Ch R = 1 ,6294    ,166.4,166.4,165.6
XS GIS Cut Line= 5
2184164.32552037 412660.991502192184021.31175886412448.847411475
2183985.13882496412275.8955712612183919.57538227412141.377473317
2183718.83965192412046.434115533
#Sta/Elev= 30
       0 2228.46   100.8 2227.14   143.4 2225.17     193    2224   276.8 2223.49
   333.2  2222.3   390.4 2222.38     412 2221.54   447.3 2222.01   453.4 2221.64
   471.2 2218.66   502.3 2217.96   515.7 2218.29   520.1 2217.89   523.2 2216.95
   524.52216.532     529 2215.06   533.5 2214.55   542.4 2215.03     546 2216.62
     549 2217.85   553.4  2218.7   581.9 2219.69   608.9 2221.66   630.9 2225.44
     645  2229.2   692.1 2244.13   747.1 2256.86   767.4 2260.76   804.2 2270.31
#Mann= 5 ,-1,0
       0     .05       0   523.2      .1       0   524.5    .045       0
     546      .1       0   630.9     .05       0
Bank Sta=524.5,546
XS Rating Curve= 0 ,0
Exp/Cntr=0.3,0.1

Type RM Length L Ch R = 1 ,6127    ,253.8,253.9,249
XS GIS Cut Line= 4
2184336.10875452412362.6940948342184132.34266681412200.374686101
 2184047.3110551 412031.728267432183870.96800234 411746.86641296
#Sta/Elev= 30
       0 2223.64    40.9 2223.31   103.5 2220.06   137.2 2219.09   211.7 2220.04
   234.4 2219.88   252.8 2220.37   264.1 2219.92   277.5 2220.44   310.7 2218.23
   328.5 2218.15   346.4 2217.41   349.4 2217.15   354.5  2215.9   358.3 2215.07
   362.6  2214.7   367.3 2214.86   371.32216.046   376.2 2217.19   389.5  2218.3
     400 2218.24   420.8 2219.03   447.7 2218.87   488.4 2217.91   523.7 2218.06
   588.8 2217.45   621.7 2217.75   678.2 2219.79   706.3 2221.97   784.4 2225.76
#Mann= 3 ,-1,0
       0     .05       0   354.5    .045       0   371.3     .05       0
#XS Ineff= 2 , 0
          298.03 2222.64     640         2222.82
Permanent Ineff=
       F       F
Bank Sta=354.5,371.3
XS Rating Curve= 0 ,0
Exp/Cntr(USF)=0,0
Exp/Cntr=0.3,0.1

Type RM Length L Ch R = 1 ,5874    ,353.9,360.1,363.6
XS GIS Cut Line= 5
2184346.30024891412360.7692564762184354.78099326412203.549703459
2184345.73775979412152.6815151612184271.13108362412018.163417217
2183993.90658871411626.827041189
#Sta/Elev= 30
       0 2223.58    35.6 2224.25   119.8  2224.1   188.3 2222.28   200.5 2222.35
   212.8 2221.86   215.8 2221.38   228.8 2217.92     236 2217.01   242.3 2216.68
   248.1  2215.7   258.9 2214.62   270.1 2215.65   281.7 2216.47   286.4 2217.54
   294.8 2217.91   368.6 2217.11   388.3 2217.71   431.8 2217.51   523.6  2215.4
     541 2215.64   579.8 2217.32   640.4 2217.34   665.6  2218.2   692.9 2220.61
   707.1 2221.28   751.4 2221.39   793.3 2222.84   819.1 2224.24   842.5 2226.59
#Mann= 3 ,-1,0
       0     .05       0   248.1    .045       0   270.1     .05       0
#XS Ineff= 2 , 0
                          648.42         2223.02
Permanent Ineff=
       F       F
Bank Sta=248.1,270.1
XS Rating Curve= 0 ,0
Exp/Cntr(USF)=0,0
Exp/Cntr=0.3,0.1

Type RM Length L Ch R = 1 ,5514    ,314.4,317.8,319.6
XS GIS Cut Line= 3
 2184654.6813565412118.3223553962184389.73353738411970.120872172
2184138.69787835411515.152860058
#Sta/Elev= 30
       0 2222.79    26.9 2221.99    76.2 2221.66   120.2 2219.25   140.4 2218.62
   202.5 2218.71   340.7 2221.12   354.9 2219.64   364.3 2219.46   370.2 2218.53
   414.4 2218.41   437.1 2216.99   458.5 2216.41   473.7 2217.03   478.3 2216.74
   485.92215.001   496.8 2212.84   510.2 2213.16     514 2214.94   520.3 2218.53
   523.9  2219.4   532.1  2219.7   633.6 2218.51   667.5 2218.64   720.8 2217.68
     750 2218.16   766.1 2219.18   776.5 2220.71   814.7 2229.78   823.2 2231.01
#Mann= 4 ,-1,0
       0     .05       0   485.9    .045       0     514     .05       0
   814.7     .06       0
#XS Ineff= 2 , 0
          334.65 2223.19
Permanent Ineff=
       F       F
Bank Sta=485.9,514
XS Rating Curve= 0 ,0
Exp/Cntr(USF)=0,0
Exp/Cntr=0.3,0.1

Type RM Length L Ch R = 1 ,5196    ,202,201.3,201.4
XS GIS Cut Line= 4
2184749.29205362412019.2938214012184618.16516822 411795.47379289
2184551.47132134411601.0442731742184542.42808788411378.354648845
#Sta/Elev= 30
       0 2224.61    72.5 2222.61   133.9 2222.47   206.4 2220.42   266.1 2220.43
   287.2 2219.15   295.7 2219.23   304.1    2218   347.8 2217.67   359.1 2215.98
   367.5 2216.16   371.8 2215.82   379.3 2213.57   384.5 2211.98   388.6 2211.63
   397.1 2212.19   400.62213.659   405.6  2217.4   409.8 2218.79   418.3 2218.85
   422.5 2219.78   439.4 2221.61   461.1  2222.6   520.9 2222.58   568.9 2223.53
   625.7  2226.3     653 2226.98     661 2228.09     673 2230.89   687.8 2235.64
#Mann= 5 ,-1,0
       0     .05       0   339.4     .06       0   379.3    .045       0
   400.6     .06       0   439.4     .05       0
#XS Ineff= 2 , 0
          297.35 2222.96
Permanent Ineff=
       F       F
Bank Sta=379.3,400.6
XS Rating Curve= 0 ,0
Exp/Cntr(USF)=0,0
Exp/Cntr=0.3,0.1

Type RM Length L Ch R = 1 ,4994    ,120,118,114.6
BEGIN DESCRIPTION:
xs 4
END DESCRIPTION:
XS GIS Cut Line= 3
2184879.28853483411903.9925945932184725.55356575411519.655171895
2184691.64144021411355.746565157
#Sta/Elev= 30
       0 2226.87      73 2225.38   148.4 2224.82   214.1 2223.59   231.4  2222.4
   248.6 2220.42   261.5 2216.12   272.3 2213.84   272.3 2213.83   278.8 2211.92
   283.1 2212.17   289.82213.789     300 2215.85   317.5 2216.19   326.1 2217.44
   334.8 2217.78   339.1 2218.58   343.4 2220.17   347.7 2221.09   361.5 2221.18
   373.5 2222.55   407.7 2224.51   481.8 2229.71   506.3 2232.69   518.6 2233.19
   534.9 2231.81   547.2 2232.19   555.4 2233.58   563.5 2235.57   581.3 2236.77
#Mann= 7 ,-1,0
       0     .05       0   272.3    .045       0   289.8     .05       0
     300     .06       0     410     .05       0  513.94      .1       0
  573.94     .05       0
Bank Sta=272.3,289.8
XS Rating Curve= 0 ,0
Exp/Cntr(USF)=0,0
Exp/Cntr=0.5,0.3