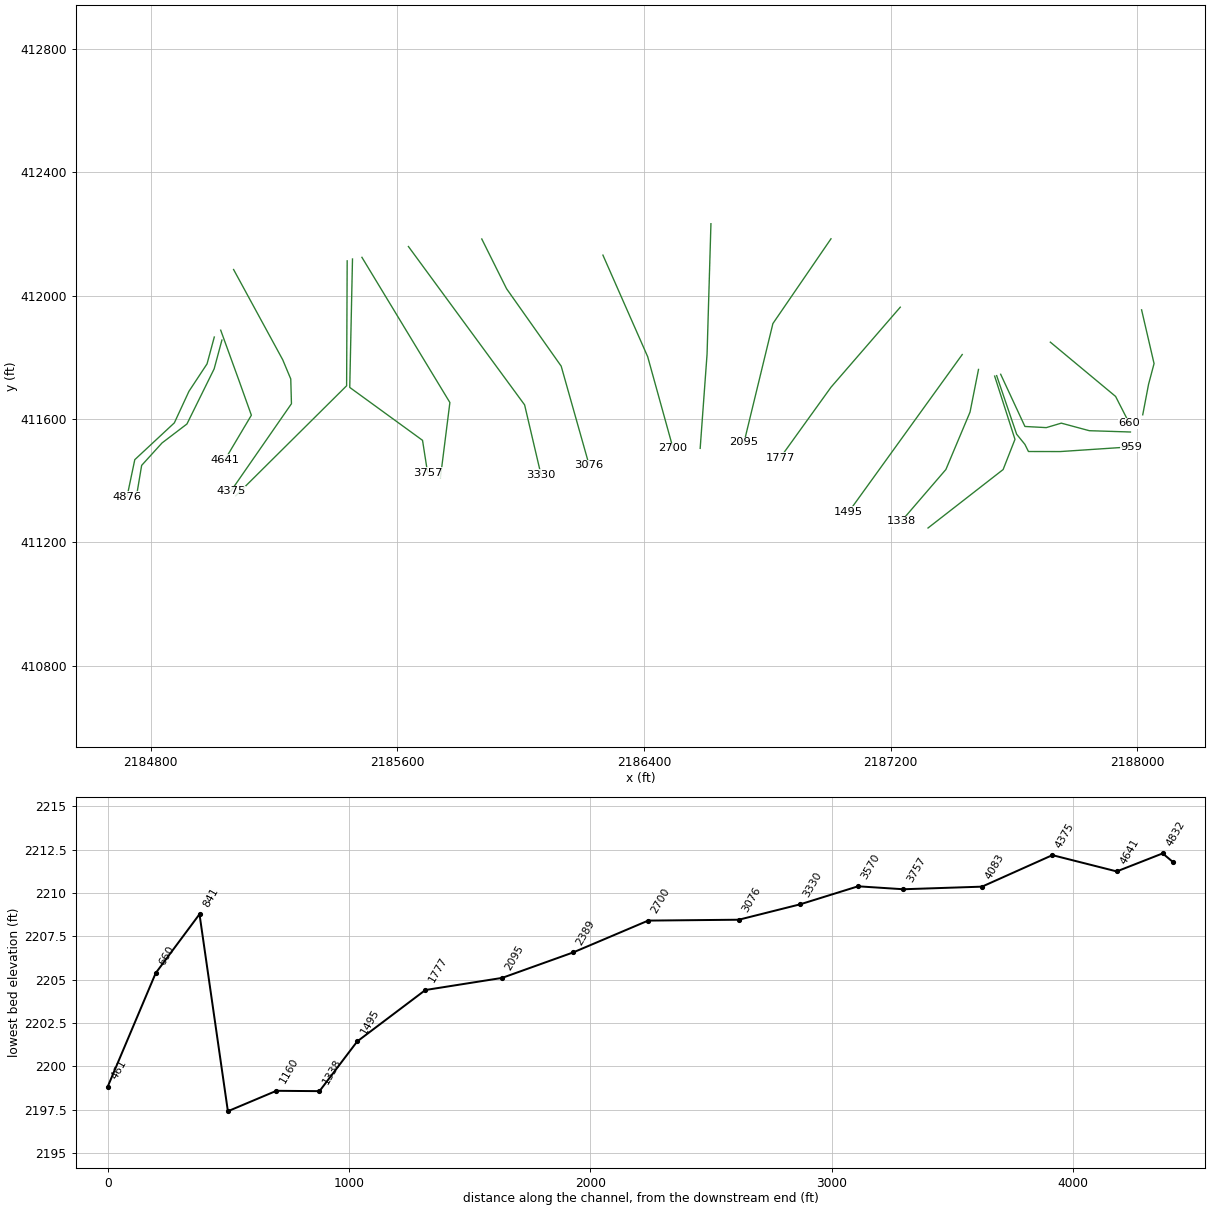
HEC-RAS study MLLSTNCK.prj: MLLSTNCK

--- MLLSTNCK.g01 (geometry) --- (continued)

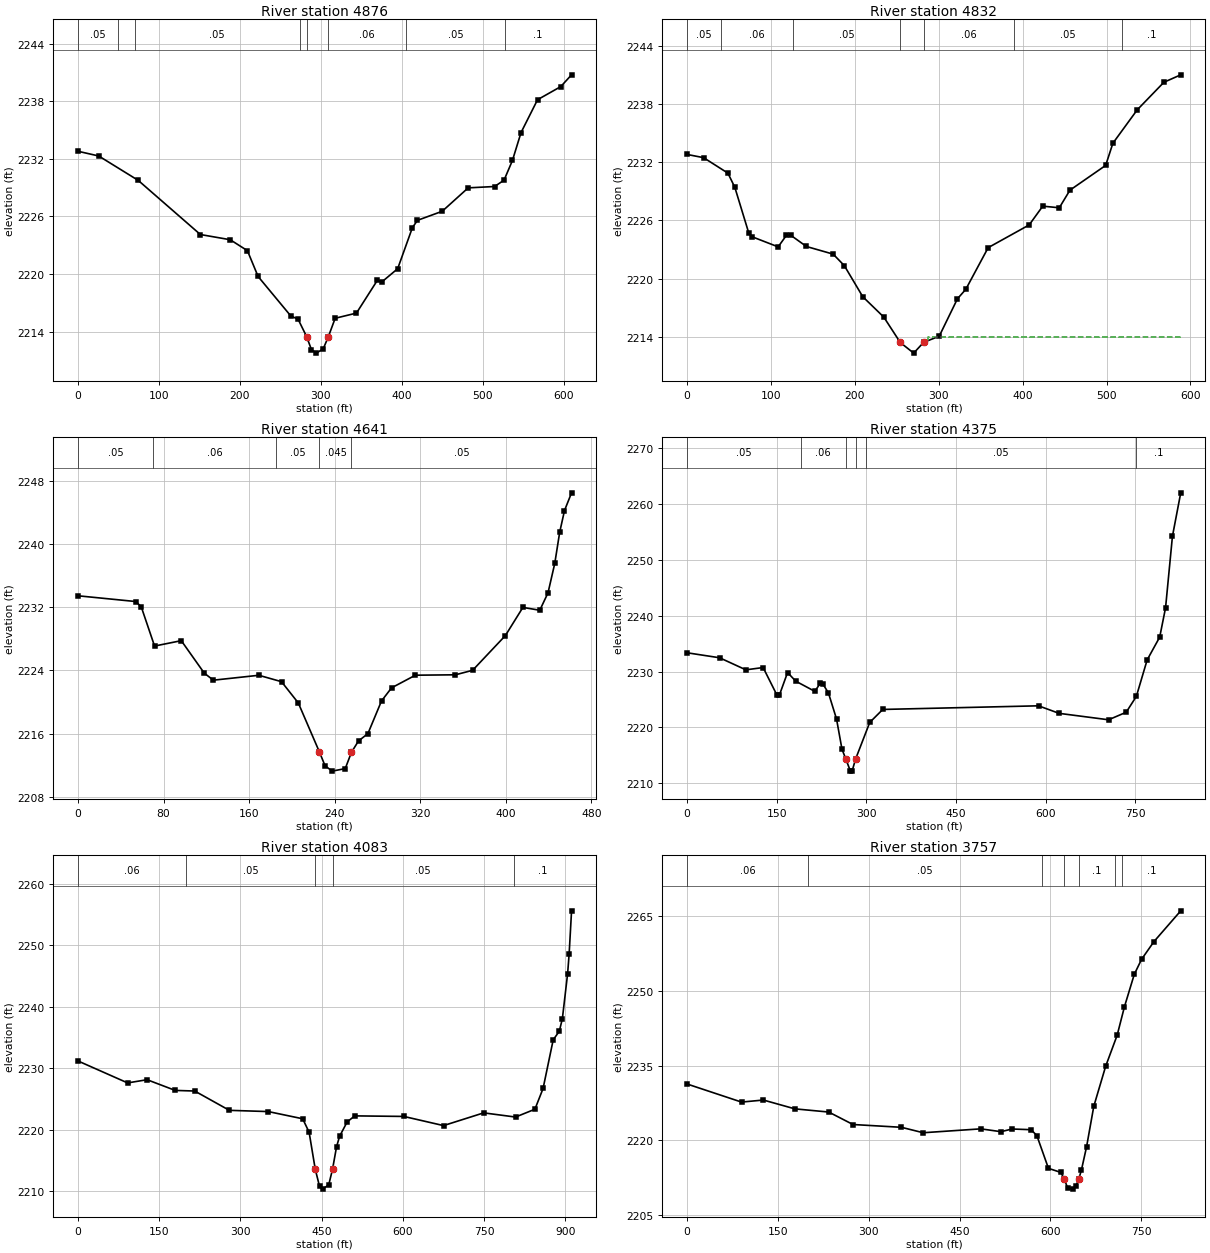
Type RM Length L Ch R = 1 ,4876    ,45.1,44.7,48.3
BEGIN DESCRIPTION:
xs 3
END DESCRIPTION:
XS GIS Cut Line= 6
2185006.59913473411865.926333957 2184983.1256136411778.965583495
2184924.36087383411689.7982840652184877.06849309411587.617771663
2184748.76162702411468.2108038152184723.54524871411348.062177782
#Sta/Elev= 30
       0 2232.79    25.6  2232.3    74.4 2229.76   151.2 2224.12     188 2223.58
   209.3 2222.44   222.5 2219.75   262.9 2215.64   271.9  2215.3   282.5 2213.48
   288.4 2212.13   294.4 2211.77   302.9 2212.21   309.2 2213.46   317.7  2215.4
     344 2215.94   369.8 2219.35   375.3 2219.18   394.9 2220.56   413.1 2224.84
   419.4  2225.6   449.9 2226.54     482 2228.98   514.6 2229.12   526.3 2229.78
   536.7 2231.84   547.3 2234.74   567.7 2238.16   596.3 2239.52   609.7 2240.75
#Mann= 8 ,-1,0
       0     .05       0      50     .06       0      70     .05       0
  273.71     .06       0   282.5    .045       0   309.2     .06       0
  405.26     .05       0  526.97      .1       0
#XS Ineff= 2 , 0
             268 2214.36     325         2214.03
Permanent Ineff=
       F       F
Bank Sta=282.5,309.2
XS Rating Curve= 0 ,0
Exp/Cntr(USF)=0,0
Exp/Cntr=0.5,0.3

Type RM Length L Ch R = 1 ,4832    ,175.9,190.2,203.2
BEGIN DESCRIPTION:
xs 2
END DESCRIPTION:
XS GIS Cut Line= 6
2185031.33339565411856.0980347762185006.11701735411762.649103416
2184917.85969329411583.9094807362184837.01895108411522.351851349
2184771.01137258 411449.669349182184756.17820887411361.412025119
#Sta/Elev= 30
       0 2232.82    19.6 2232.49    48.6 2230.89    56.9 2229.41    73.4 2224.72
    77.6 2224.31   108.5 2223.27   118.4 2224.47   123.4 2224.48   142.2 2223.31
   174.1 2222.52   187.4 2221.33   209.4 2218.12   234.5 2216.01   254.1 2213.39
   270.1 2212.29     282 2213.41   300.5 2214.03   322.3 2217.91   332.2 2218.88
   358.9 2223.19   407.8 2225.54     424 2227.48   443.7 2227.31   456.4 2229.13
     499 2231.69   507.6 2233.98   536.6 2237.43   568.4 2240.28   588.5 2241.05
#Mann= 7 ,-1,0
       0     .05       0      40     .06       0  126.79     .05       0
   254.1    .045       0     282     .06       0  389.34     .05       0
  518.98      .1       0
#XS Ineff= 2 , 0
             249    2214     287            2214
Permanent Ineff=
       F       F
Bank Sta=254.1,282
XS Rating Curve= 0 ,0
Exp/Cntr(USF)=0,0
Exp/Cntr=0.5,0.3

Type RM Length L Ch R = 1 ,4641    ,254.4,266.7,272.5
BEGIN DESCRIPTION:
xs 1
END DESCRIPTION:
XS GIS Cut Line= 4
2185027.37148298411888.1669360112185087.28290476411723.127925088
2185126.84705121411612.348315017 2185040.9363332411467.656579414
#Sta/Elev= 30
       0 2233.44    54.2 2232.71    59.2 2232.03    71.6 2227.08    96.6 2227.76
   118.1 2223.65   126.6 2222.76   169.1 2223.38   190.3 2222.57     206 2219.88
   225.8 2213.66     231 2211.93   237.7 2211.25   249.9 2211.57   255.72213.633
   262.3 2215.07   271.1    2216   283.8 2220.13   293.2 2221.79   315.5 2223.39
   352.9 2223.44     369 2224.01   399.6  2228.4     416 2231.97   431.8 2231.61
   439.5 2233.82   445.8 2237.54   450.4 2241.48   454.9 2244.23   461.5 2246.47
#Mann= 5 ,-1,0
       0     .05       0      70     .06       0  185.58     .05       0
   225.8    .045       0   255.7     .05       0
Bank Sta=225.8,255.7
XS Rating Curve= 0 ,0
Exp/Cntr(USF)=0,0
Exp/Cntr=0.3,0.1

Type RM Length L Ch R = 1 ,4375    ,308.3,291.5,274.1
XS GIS Cut Line= 5
 2185069.1964378412084.8572640972185228.58342781411792.082580337
2185254.58272405411729.9103501942185256.84353242411649.651653102
2185060.15320432411365.920202817
#Sta/Elev= 30
       0 2233.37    54.3 2232.48    98.3 2230.32   127.2 2230.73   149.9 2225.89
   154.5 2225.82   168.1 2229.84   181.8 2228.29   213.7 2226.47   222.8  2227.9
   227.4 2227.76   236.5 2226.19   250.1 2221.51   259.2 2216.11   265.6 2214.37
   273.3 2212.19   276.2 2212.22     282 2214.36   305.7 2220.91   327.5 2223.23
   588.2 2223.88   622.7 2222.53   705.5 2221.38     735 2222.73     752 2225.57
   770.1  2232.1   791.1 2236.18   800.9 2241.43   812.4 2254.22   826.3    2262
#Mann= 6 ,-1,0
       0     .05       0     190     .06       0   265.6    .045       0
     282     .06       0     300     .05       0  751.03      .1       0
Bank Sta=265.6,282
XS Rating Curve= 0 ,0
Exp/Cntr(USF)=0,0
Exp/Cntr=0.3,0.1

Type RM Length L Ch R = 1 ,4083    ,299,326,359.2
XS GIS Cut Line= 3
2185437.56977531412112.9093363562185435.75555583411707.887359836
2185076.12184567411350.854292087
#Sta/Elev= 30
       0 2231.21    91.7 2227.64   127.7 2228.16   179.7 2226.42   215.7 2226.32
   279.7 2223.18   351.6 2222.98   415.1 2221.81     427 2219.62   438.3 2213.61
   446.2 2210.83   451.9 2210.37   463.2 2211.06   470.32213.625   477.7 2217.27
   483.3 2218.96   497.2 2221.29   511.3 2222.28   601.9 2222.19   675.3  2220.7
   749.5 2222.77   808.3 2222.09   844.1 2223.36   859.2 2226.74   877.9 2234.65
   889.2 2236.05   894.8 2238.07   904.5 2245.39   907.3 2248.56   911.8 2255.62
#Mann= 5 ,-1,0
       0     .06       0     200     .05       0   438.3    .045       0
   470.3     .05       0  805.03      .1       0
Bank Sta=438.3,470.3
XS Rating Curve= 0 ,0
Exp/Cntr(USF)=0,0
Exp/Cntr=0.3,0.1

Type RM Length L Ch R = 1 ,3757    ,196.8,187.4,180.2
XS GIS Cut Line= 4
2185454.81891529412118.9916371712185445.91523788411702.486539844
2185681.94899004411530.9240297292185698.42479962411425.374217129
#Sta/Elev= 30
       0  2231.3    89.8 2227.68   125.9 2228.09   177.9 2226.32   233.9 2225.68
   273.9 2223.18   353.9 2222.62   389.9 2221.53     485 2222.31   518.3 2221.74
   536.6 2222.28   568.1 2222.14   577.6 2220.95   596.7 2214.39   617.2 2213.57
     6232212.179   628.2 2210.51   636.8 2210.22   641.9 2210.76   646.82212.249
   651.1 2214.01   659.7 2218.72   671.6 2226.83   691.2 2234.86   710.2 2241.09
   722.3 2246.83   738.5 2253.31   750.6 2256.33   770.9 2259.86   815.2 2266.04
#Mann= 7 ,-1,0
       0     .06       0     200     .05       0   586.6      .1       0
     623    .045       0   646.8      .1       0   706.6     .05       0
   718.4      .1       0
Bank Sta=623,646.8
XS Rating Curve= 0 ,0
Exp/Cntr(USF)=0,0
Exp/Cntr=0.3,0.1

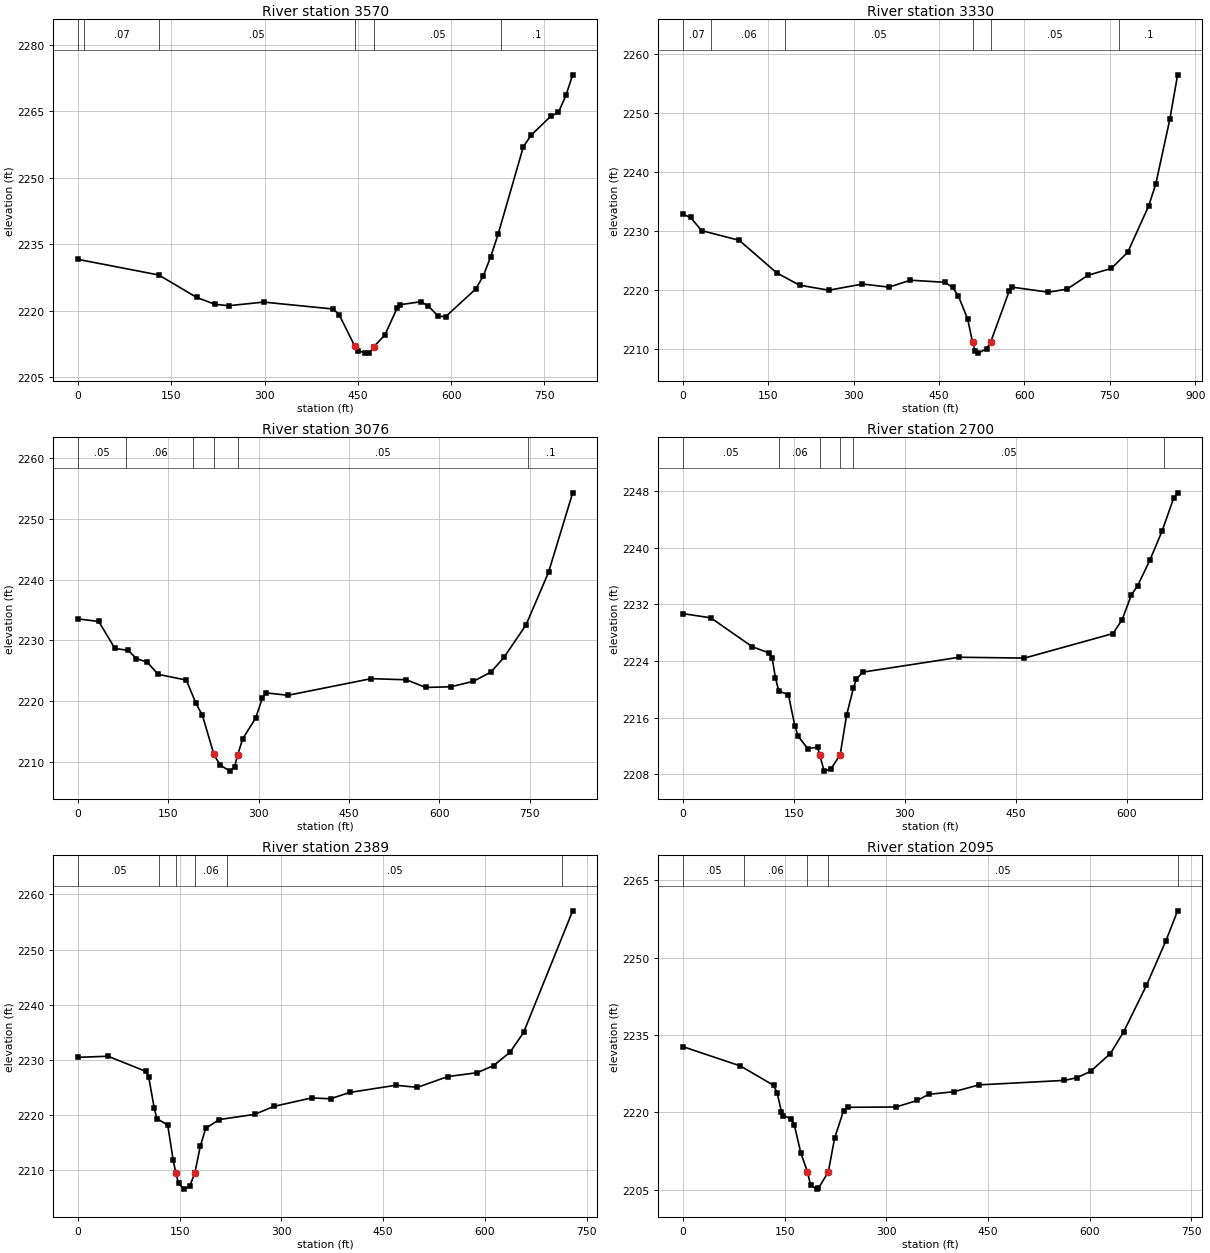
Type RM Length L Ch R = 1 ,3570    ,238.2,240,242.6
XS GIS Cut Line= 3
2185485.42851062 412124.395432832185770.66657304411653.465477431
2185740.03698244411410.343102083
#Sta/Elev= 30
       0 2231.55     130 2228.02   190.7 2222.97   219.9 2221.42   242.3 2221.09
   298.5 2221.91   410.6 2220.34     420 2219.05   445.4 2211.89   449.9 2210.96
   462.1 2210.39   468.6 2210.49   475.8 2211.82   493.6 2214.51   513.5 2220.63
   518.2 2221.32   550.9 2221.98     563 2221.09   579.1 2218.74   591.2 2218.61
   639.6 2224.86   651.7 2227.77   663.8 2232.15   675.8 2237.29   716.2 2256.94
   728.5 2259.54   760.2 2263.83   772.6 2264.71   784.7 2268.55   795.6  2273.2
#Mann= 6 ,-1,0
       0     .06       0      10     .07       0     130     .05       0
   445.4    .045       0   475.8     .05       0  680.58      .1       0
Bank Sta=445.4,475.8
XS Rating Curve= 0 ,0
Exp/Cntr(USF)=0,0
Exp/Cntr=0.3,0.1

Type RM Length L Ch R = 1 ,3330    ,263.9,254.3,256.5
XS GIS Cut Line= 3
2185636.24180908412159.4628980942186013.04320388411645.896552587
 2186066.0745113411419.815715706
#Sta/Elev= 30
       0 2232.85    13.4 2232.31    32.6 2230.09    98.9 2228.44   164.7 2222.94
   204.8 2220.85   256.3    2220   315.4 2221.04   362.1 2220.52   399.7 2221.69
   459.7 2221.34   473.8 2220.49   484.1 2218.97   500.3 2215.12   508.9 2211.15
   513.8 2209.69   518.8 2209.35   533.8  2210.1   540.8 2211.26   573.4 2219.88
   578.3 2220.52   641.8 2219.67   674.7 2220.17   711.7 2222.53   752.7 2223.68
   781.5 2226.42   818.5  2234.3   830.8 2237.97   855.5 2248.92   869.2 2256.45
#Mann= 6 ,-1,0
       0     .07       0      50     .06       0     180     .05       0
   508.9    .045       0   540.8     .05       0  766.97      .1       0
Bank Sta=508.9,540.8
XS Rating Curve= 0 ,0
Exp/Cntr(USF)=0,0
Exp/Cntr=0.3,0.1

Type RM Length L Ch R = 1 ,3076    ,390,375.4,373.3
XS GIS Cut Line= 4
2185874.10117844412183.9549887552185954.42965358412022.697947388
2186131.66586521411771.497017521 2186222.3773121411450.518051579
#Sta/Elev= 30
       0 2233.54    34.4 2233.12    61.2 2228.68    83.5 2228.35    96.9 2226.99
   114.8 2226.43   132.7 2224.42   179.7 2223.46   195.8 2219.63   206.5 2217.64
   225.6 2211.21   235.9 2209.43   252.6 2208.46     260  2209.2   264.82211.079
   273.4 2213.81   294.6 2217.15   305.9 2220.45   311.7 2221.36   348.5 2220.96
   486.7  2223.7     545 2223.51   577.3 2222.25   618.9 2222.36   656.3 2223.26
   685.4 2224.78     707  2227.2   743.6 2232.55     781 2241.22   821.1 2254.32
#Mann= 6 ,-1,0
       0     .05       0      80     .06       0  190.16     .05       0
   225.6    .045       0   264.8     .05       0  747.59      .1       0
Bank Sta=225.6,264.8
XS Rating Curve= 0 ,0
Exp/Cntr(USF)=0,0
Exp/Cntr=0.3,0.1

Type RM Length L Ch R = 1 ,2700    ,316.6,311.1,297.5
XS GIS Cut Line= 3
2186267.03525519412131.5516836642186412.17357023411802.199353394
2186494.51165279411504.944919717
#Sta/Elev= 30
       0  2230.7    37.6 2230.11    93.7 2226.01   116.2 2225.14   120.6 2224.36
     125  2221.6   129.4 2219.76   142.5 2219.22   151.2  2214.8   155.6 2213.36
   168.7 2211.59   181.8  2211.8   184.7 2210.74   190.8 2208.41   199.9 2208.72
   212.4 2210.71   221.1 2216.33   230.2 2220.11   234.3 2221.44     243 2222.42
   373.4 2224.53   461.5 2224.41     581 2227.88   593.4 2229.84   605.9 2233.35
   614.2 2234.62   630.8 2238.24   647.4 2242.39     663 2247.04   668.4  2247.8
#Mann= 6 ,-1,0
       0     .05       0     130     .06       0   184.7    .045       0
   212.4     .06       0     230     .05       0  649.91      .1       0
Bank Sta=184.7,212.4
XS Rating Curve= 0 ,0
Exp/Cntr(USF)=0,0
Exp/Cntr=0.3,0.1

Type RM Length L Ch R = 1 ,2389    ,304.1,294.2,281.2
XS GIS Cut Line= 3
2186617.32099628412233.4276163332186604.76094979411810.572717722
2186582.43197825411504.944919717
#Sta/Elev= 30
       0 2230.46    44.3 2230.66   100.3  2227.9   104.3 2226.84   112.3 2221.32
   116.3 2219.36   132.3 2218.17   140.3 2211.85   144.3 2209.45   148.3 2207.61
   156.3 2206.57   164.6 2207.06   172.3 2209.52   172.3 2209.53   180.3 2214.32
   188.3 2217.59   208.3 2219.18   260.4 2220.12   288.9 2221.57   344.4  2223.1
   372.4 2222.95   400.4 2224.09   468.6  2225.4   500.6 2225.02   545.1 2226.97
   588.9 2227.68   612.9 2228.98     637 2231.37   657.1 2234.97   729.5 2257.02
#Mann= 6 ,-1,0
       0     .05       0     120     .06       0   144.3    .045       0
   172.3     .06       0     220     .05       0  713.04      .1       0
Bank Sta=144.3,172.3
XS Rating Curve= 0 ,0
Exp/Cntr(USF)=0,0
Exp/Cntr=0.3,0.1

Type RM Length L Ch R = 1 ,2095    ,317.7,317.8,312.4
XS GIS Cut Line= 3
2187006.68243758412184.5829910812186818.28174018411909.657528948
2186724.77917184411524.482769818
#Sta/Elev= 30
       0 2232.73    84.8 2228.99   133.7 2225.23   138.9  2223.8   145.2 2220.15
   148.1 2219.36   159.3 2218.77   164.1 2217.63   173.8 2212.16   183.5  2208.5
   188.4 2205.81     197  2205.1   199.9 2205.29   214.3 2208.39   223.8 2215.03
   236.9 2220.31   243.1 2220.97   314.5 2221.03   345.4  2222.3   362.6 2223.49
   399.6 2223.99   436.7 2225.32   562.6 2226.19   581.1 2226.71   601.3 2227.95
   630.5  2231.4   650.1 2235.62   683.7 2244.64   712.5  2253.3   729.6 2259.08
#Mann= 5 ,-1,0
       0     .05       0      90     .06       0   183.5    .045       0
   214.3     .05       0  729.65      .1       0
Bank Sta=183.5,214.3
XS Rating Curve= 0 ,0
Exp/Cntr(USF)=0,0
Exp/Cntr=0.3,0.1

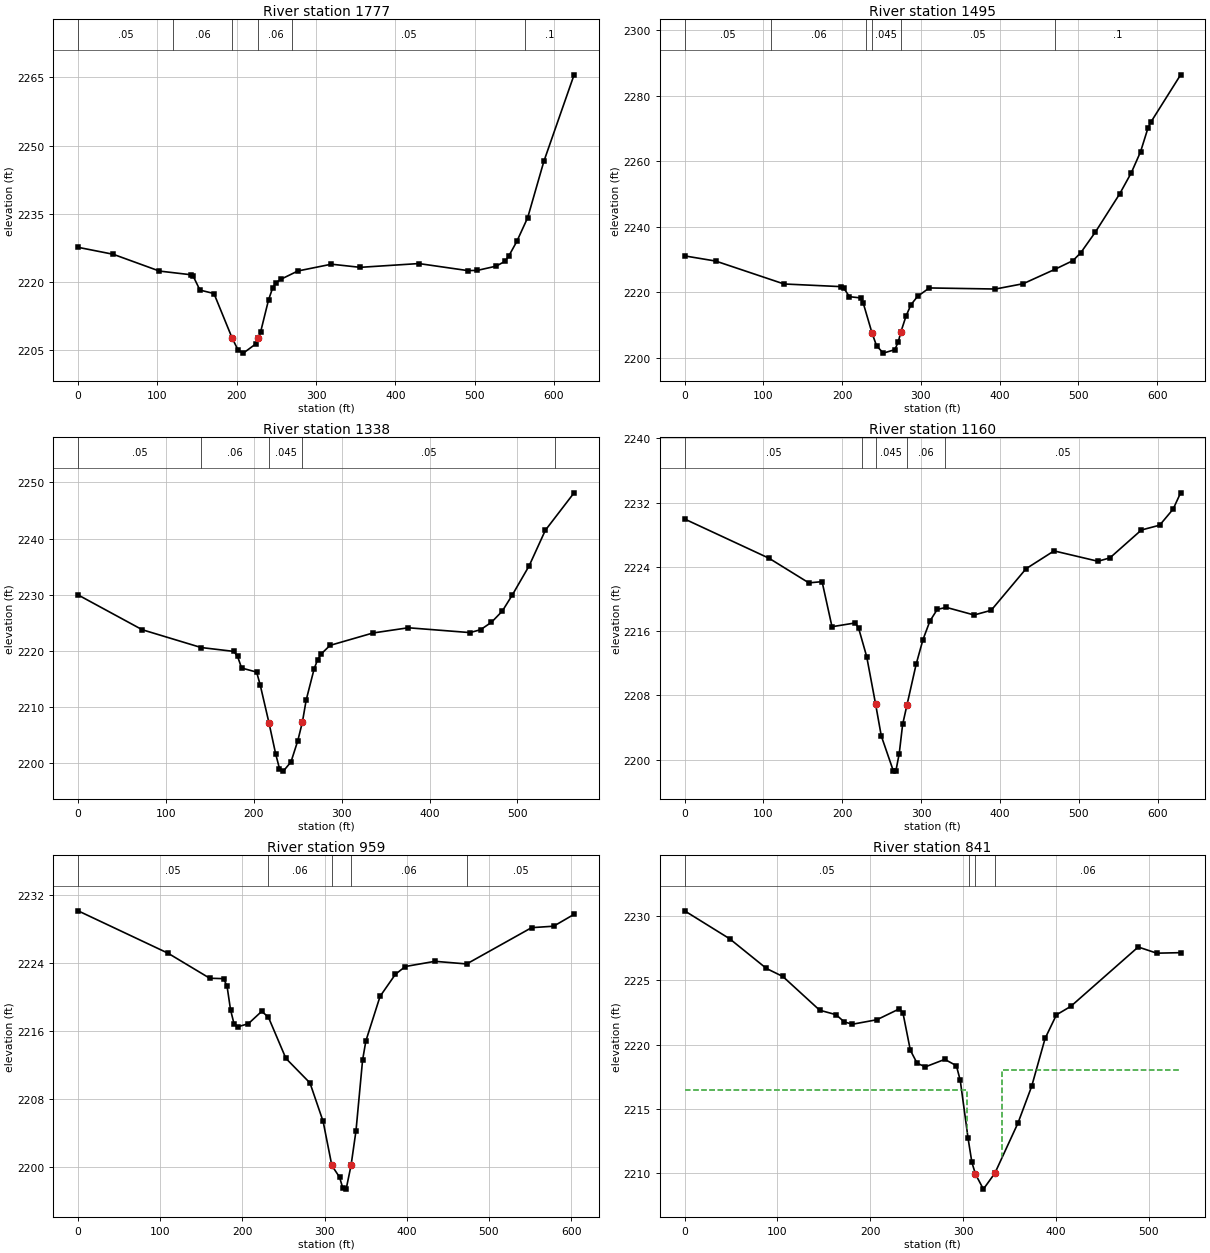
Type RM Length L Ch R = 1 ,1777    ,278.7,282.5,283.2
XS GIS Cut Line= 3
2187231.36771374411962.6888363642187006.68243758411703.114542168
2186842.00627244411474.242583844
#Sta/Elev= 30
       0 2227.66    44.3 2226.13   102.5 2222.44   142.3 2221.63   145.1 2221.32
   153.6 2218.26   171.3  2217.5   194.3 2207.67   201.8 2205.04   208.3  2204.4
   224.2 2206.45   227.4 2207.66   230.2 2209.12   240.1  2216.1   245.4 2218.79
     250 2219.92   255.7 2220.64   277.1 2222.46   319.4 2223.95   355.6 2223.26
   429.6 2224.09   491.4 2222.54   503.4 2222.59     527 2223.52   537.9 2224.55
   542.8 2225.69   553.1 2228.96   566.8 2234.18   587.2 2246.56   625.3 2265.58
#Mann= 6 ,-1,0
       0     .05       0     120     .06       0   194.3    .045       0
   227.4     .06       0     270     .05       0  563.31      .1       0
Bank Sta=194.3,227.4
XS Rating Curve= 0 ,0
Exp/Cntr(USF)=0,0
Exp/Cntr=0.3,0.1

Type RM Length L Ch R = 1 ,1495    ,150.2,156.2,160.9
XS GIS Cut Line= 2
2187432.32845763411809.1771570012187063.90042716411298.401932937
#Sta/Elev= 30
       0  2231.1    39.5 2229.52   126.2 2222.53   198.6 2221.72   202.2 2221.23
   209.3 2218.65   223.6 2218.27   226.9 2216.62   237.9 2207.61   243.7 2203.68
   252.3 2201.43   266.9 2202.49   271.3 2204.88   274.5 2207.82   281.1  2212.7
   287.4  2216.2   295.9 2218.77   310.7 2221.32   394.6 2220.99   429.9 2222.61
     470 2226.98   493.2 2229.67   503.1 2232.09   521.6 2238.38   552.4 2250.01
   567.2 2256.48   578.9 2262.85   588.3 2270.08   591.8 2271.83   629.8 2286.35
#Mann= 6 ,-1,0
       0     .05       0     110     .06       0     230     .05       0
   237.9    .045       0   274.5     .05       0     470      .1       0
Bank Sta=237.9,274.5
XS Rating Curve= 0 ,0
Exp/Cntr(USF)=0,0
Exp/Cntr=0.3,0.1

Type RM Length L Ch R = 1 ,1338    ,174.1,178.5,175.5
XS GIS Cut Line= 4
2187485.11372864411760.8165039042187457.64490696411622.455031733
2187379.30789698411436.2774625612187234.84224222411268.412441177
#Sta/Elev= 30
       0 2229.95      73 2223.75     140 2220.58   177.2 2219.89   181.5 2218.99
   186.1 2216.93   203.2  2216.2   207.3 2213.89   217.22207.198   224.9  2201.6
   229.2 2199.02   233.6 2198.56   242.3  2200.2   250.1 2204.01   255.3 2207.31
   259.6 2211.23   268.6 2216.75   272.6 2218.41     277 2219.48   286.7 2220.96
   335.6 2223.17   375.8  2224.1     446 2223.24     458 2223.75   470.5 2225.08
   482.8 2227.07   494.2 2229.94   513.4 2235.15   531.8 2241.47   564.5 2248.14
#Mann= 5 ,-1,0
       0     .05       0     140     .06       0   217.2    .045       0
   255.3     .05       0  543.05      .1       0
Bank Sta=217.2,255.3
XS Rating Curve= 0 ,0
Exp/Cntr(USF)=0,0
Exp/Cntr=0.3,0.1

Type RM Length L Ch R = 1 ,1160    ,100.6,201,227.8
BEGIN DESCRIPTION:
xs 4
END DESCRIPTION:
XS GIS Cut Line= 4
2187537.47513226411739.2267120432187603.40030429411534.126176825
2187564.94395394411436.1540461632187321.38706837411246.619176564
#Sta/Elev= 30
       0 2229.97   107.2 2225.08   157.6 2222.02   174.4 2222.17     187 2216.56
   216.5 2217.03   220.7  2216.4     231 2212.84   242.2 2206.98   249.5 2202.97
   264.9 2198.58   268.1 2198.64   272.3 2200.77   276.6 2204.39   282.1 2206.81
   293.8 2211.91   302.4 2214.95   311.2 2217.26   320.5 2218.71   331.9 2218.97
   367.3 2218.02   388.9  2218.6   433.2 2223.78   468.7    2226   524.4 2224.71
   539.6 2225.13   579.5  2228.6   602.7  2229.2   619.8  2231.2   629.3 2233.23
#Mann= 5 ,-1,0
       0     .05       0  225.44     .06       0   242.2    .045       0
   282.1     .06       0  330.68     .05       0
Bank Sta=242.2,282.1
XS Rating Curve= 0 ,0
Exp/Cntr(USF)=0,0
Exp/Cntr=0.5,0.2

Type RM Length L Ch R = 1 ,959     ,138.8,117.6,114.1
BEGIN DESCRIPTION:
xs 3
END DESCRIPTION:
XS GIS Cut Line= 6
2187543.97331535411740.7946816482187608.78391938 411550.75821247
2187635.63857807411517.7058918242187647.09083524411494.646673752
2187750.47715485411494.502869111 2187981.0975016 411509.87875475
#Sta/Elev= 30
       0 2230.14   109.5 2225.15   160.2 2222.21   177.1 2222.16   181.3 2221.26
   185.5 2218.51   189.8 2216.83     194 2216.49   207.2 2216.86   223.4 2218.31
   231.5 2217.65   252.9 2212.78   282.2 2209.89   298.2 2205.36   308.8 2200.18
   318.2  2198.8   322.2  2197.5   326.2  2197.4   332.22200.205   338.2 2204.27
   346.2 2212.57   350.2 2214.83   367.5 2220.08   386.2 2222.68   398.3 2223.59
   434.3  2224.2   472.9 2223.89   551.9 2228.16   578.7 2228.33   603.6 2229.73
#Mann= 5 ,-1,0
       0     .05       0   231.5     .06       0   308.8    .045       0
   332.2     .06       0   472.9     .05       0
#XS Ineff= 2 , 0
           230.8 2216.86   408.2         2218.58
Permanent Ineff=
       F       F
Bank Sta=308.8,332.2
XS Rating Curve= 0 ,0
Exp/Cntr(USF)=0,0
Exp/Cntr=0.5,0.3

Type RM Length L Ch R = 1 ,841     ,185.5,181.4,171
BEGIN DESCRIPTION:
xs 2
END DESCRIPTION:
XS GIS Cut Line= 6
2187557.00807401411745.1389730342187635.68183751411575.870078164
2187704.91346696411572.1446880732187753.62087711 411586.65066483
2187844.39106688411562.1762851782187977.89190655411557.932488949
#Sta/Elev= 30
       0  2230.4    48.5 2228.23    88.2 2225.92   105.8  2225.3   145.5 2222.68
   163.2 2222.33     172 2221.77   180.8 2221.59   207.2 2221.94   231.5 2222.79
   235.2 2222.48   243.2 2219.57   250.5 2218.56   259.4 2218.28   280.3 2218.86
   292.8 2218.37     297 2217.22   305.3 2212.78   309.5 2210.86   313.4 2209.94
   321.9 2208.78   334.3 2210.02   359.2 2213.92   373.9 2216.76   388.4 2220.49
   400.6 2222.32   416.1 2222.98   488.7 2227.59   508.7 2227.11   534.4 2227.15
#Mann= 4 ,-1,0
       0     .05       0  305.99     .06       0   313.4    .045       0
   334.3     .06       0
#XS Ineff= 2 , 0
           304.6  2216.5   341.7            2218
Permanent Ineff=
       F       F
Bank Sta=313.4,334.3
XS Rating Curve= 0 ,0
Exp/Cntr(USF)=0,0
Exp/Cntr=0.5,0.3

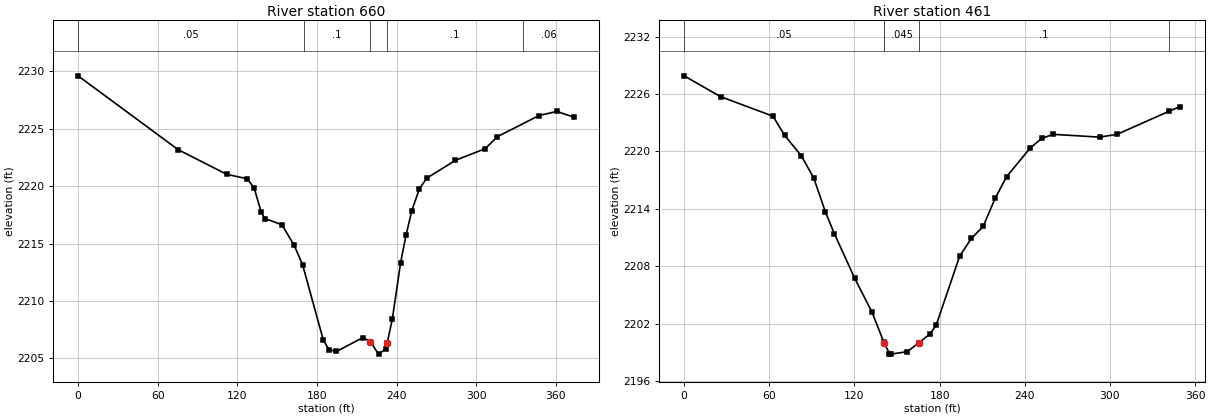
Type RM Length L Ch R = 1 ,660     ,206.2,199.2,188.3
XS GIS Cut Line= 3
2187718.09003105411849.3271515422187929.70169437411673.323220031
2187974.46570007411585.829936158
#Sta/Elev= 30
       0 2229.62    75.4 2223.19     112 2221.04   127.6 2220.65   132.8 2219.81
     138 2217.74   140.8 2217.19   153.6 2216.65   162.9 2214.85   169.2 2213.16
   184.8 2206.61     189 2205.77   194.7 2205.61   214.6 2206.82   220.3 2206.47
   226.4 2205.38   231.7 2205.81     2332206.391   236.8 2208.43     243 2213.31
   247.2 2215.78   251.5 2217.88   257.2 2219.78   262.8 2220.71   284.4 2222.26
   306.9 2223.28   315.8 2224.31   347.3 2226.16   360.8 2226.52   373.5 2226.02
#Mann= 5 ,-1,0
       0     .05       0     170      .1       0   220.3    .045       0
     233      .1       0  335.24     .06       0
Bank Sta=220.3,233
XS Rating Curve= 0 ,0
Exp/Cntr(USF)=0,0
Exp/Cntr=0.3,0.1

Type RM Length L Ch R = 1 ,461     ,237.8,238.6,211.7
XS GIS Cut Line= 4
2188014.01875422411954.1654345322188054.49073744411779.831762977
2188036.63440211411712.618420312 2188017.7639215411613.717578279
#Sta/Elev= 30
       0 2227.91    25.7 2225.73    62.6 2223.69    70.8 2221.69    82.6 2219.54
    91.4 2217.21    99.6 2213.65   105.9 2211.39   120.1 2206.77   132.4 2203.19
   140.6  2200.1     141 2199.98   144.7 2198.86   145.9 2198.81   157.1 2199.07
   165.3 2199.97   173.5 2200.96   177.6 2201.84   194.1 2209.04   202.4 2210.91
   210.7 2212.16   219.1 2215.09   227.2 2217.36   243.8 2220.36     252 2221.38
   260.2 2221.79   292.7  2221.5     305 2221.79   341.6  2224.2   349.2 2224.68
#Mann= 5 ,-1,0
       0     .05       0   140.6      .1       0     141    .045       0
   165.3      .1       0   341.6     .06       0
Bank Sta=141,165.3
XS Rating Curve= 0 ,0
Exp/Cntr(USF)=0,0
Exp/Cntr=0.3,0.1