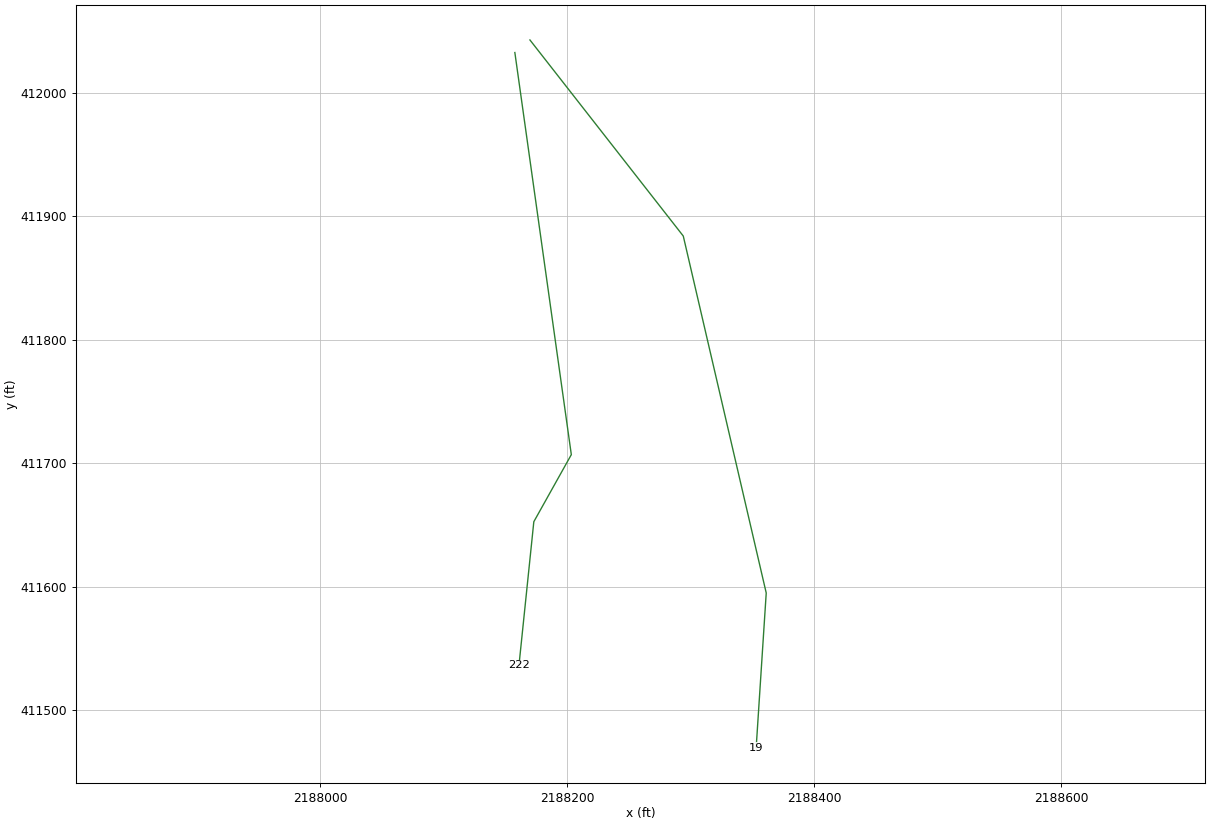
HEC-RAS study MLLSTNCK.prj: MLLSTNCK

--- MLLSTNCK.g01 (geometry) --- (continued)

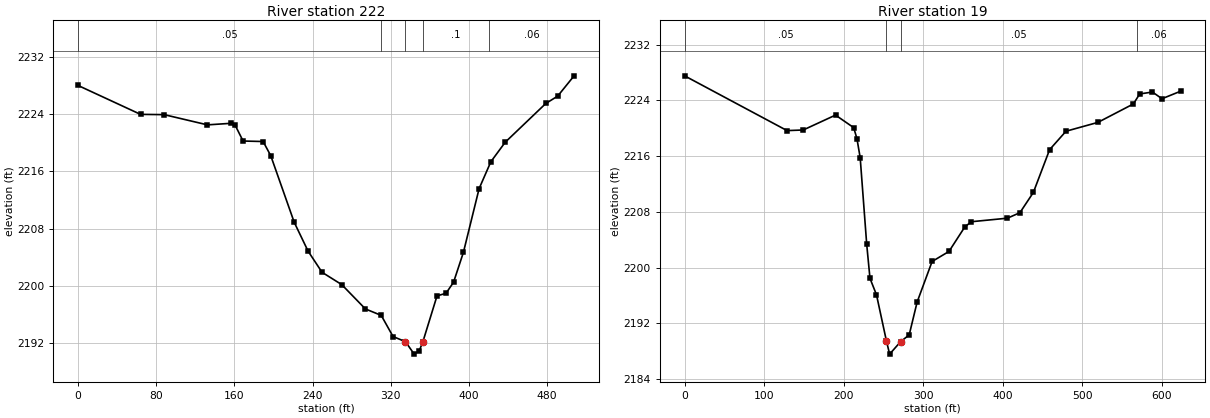
Type RM Length L Ch R = 1 ,222     ,203.2,203.2,203.2
XS GIS Cut Line= 4
2188157.59117794412032.4526294162188203.29811781411706.960134277
2188172.94587153411652.6762641432188160.91985901411536.485624533
#Sta/Elev= 30
       0 2228.01    63.9 2223.97    88.1 2223.93   132.4  2222.5   156.8 2222.72
   160.8 2222.44   168.9 2220.24   189.4 2220.17   197.2 2218.19   221.2 2208.88
   235.4 2204.84   249.7 2201.88   269.9 2200.15   294.1 2196.75   310.3 2195.85
   322.4 2192.89   335.1 2192.17     344 2190.43   349.1 2190.87   352.9 2192.15
   367.4 2198.58   376.6 2198.94   384.3 2200.48   394.4 2204.66   410.5 2213.59
   422.5 2217.34   437.2 2220.07   478.8  2225.5   490.9 2226.52   507.7 2229.36
#Mann= 5 ,-1,0
       0     .05       0     310      .1       0   335.1    .045       0
   352.9      .1       0  420.88     .06       0
Bank Sta=335.1,352.9
XS Rating Curve= 0 ,0
Exp/Cntr(USF)=0,0
Exp/Cntr=0.3,0.1

Type RM Length L Ch R = 1 ,19      ,,,
XS GIS Cut Line= 4
2188169.79954314412042.6262670762188293.91792258411883.917519585
2188361.06393114411594.9862100522188352.92502101411469.850466838
#Sta/Elev= 30
       0 2227.54   128.8 2219.67   149.1 2219.76   189.7  2221.9   212.5  2220.1
   216.6 2218.53   220.7 2215.78   228.9 2203.33     233 2198.45   241.2 2196.08
   253.6  2189.5   257.7 2187.56   271.7 2189.37   282.3 2190.32   292.3 2195.05
   311.1 2200.87   332.3 2202.31   352.1 2205.81   360.3 2206.58   405.8 2207.09
   421.5 2207.88   438.4 2210.79   458.8 2216.93   479.4 2219.58   519.5 2220.85
   564.1  2223.5   572.1 2224.94   588.1 2225.21   600.1 2224.25   623.5 2225.33
#Mann= 4 ,-1,0
       0     .05       0   253.6    .045       0   271.7     .05       0
  568.11     .06       0
Bank Sta=253.6,271.7
XS Rating Curve= 0 ,0
Exp/Cntr(USF)=0,0
Exp/Cntr=0.3,0.1
LCMann Table=0

Chan Stop Cuts=-1
Use User Specified Reach Order=0
Composite Channel Slope=5